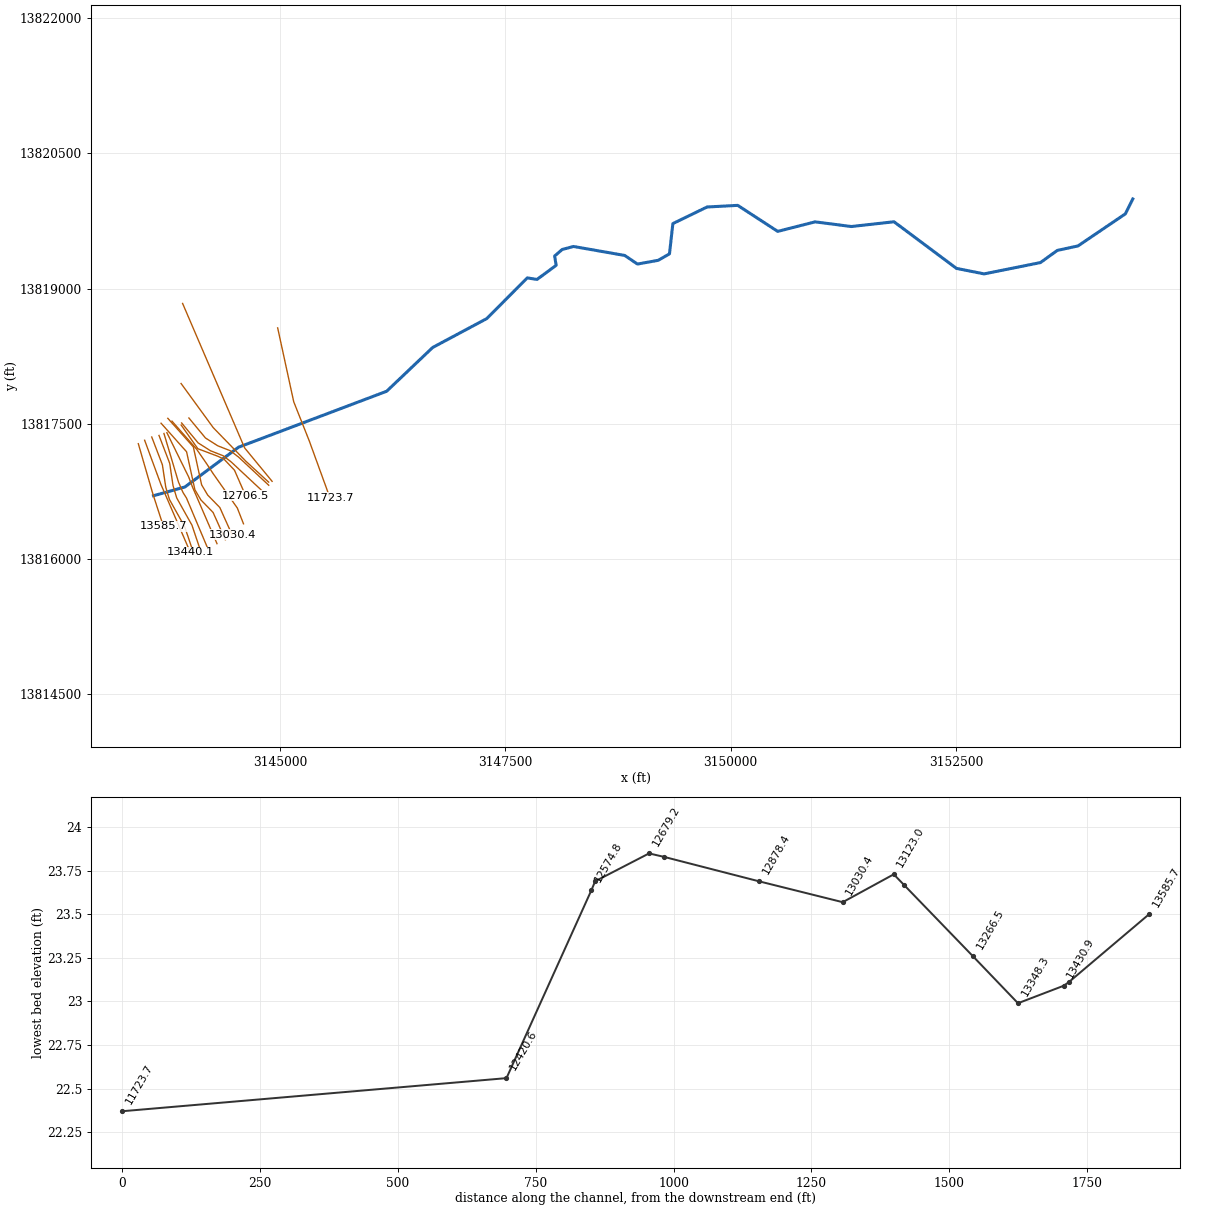
--- C103-00-00.PRJ (project) ---

Proj Title=C103-00-00
Current Plan=p02
Default Exp/Contr=0.3,0.1
English Units
Geom File=g01
Flow File=f01
Flow File=f02
Plan File=p01
Plan File=p02
Y Axis Title=Elevation
X Axis Title(PF)=Main Channel Distance
X Axis Title(XS)=Station
BEGIN DESCRIPTION:
Sims Bayou Watershed
Pine Gully
HCFCD Unit C103-00-00
Flood Hazard Model
10, 2, 1, 0.2% Event
Filename C103-00-00.prj
Prepared by:  Watershed Concepts  Date:
Reviewed by:                      Date:
STATUS FINAL
END DESCRIPTION:
DSS Export Rating Curves= 0
DSS Export Rating Curve Sorted= 0
DSS Export Volume Flow Curves= 0
DXF OffsetX= 0
DXF OffsetY= 0
DXF ScaleX= 1
DXF ScaleY= 10

--- C103-00-00.p02 (plan) ---

Plan Title=Effective Floodway 2015
Program Version=4.10
Short Identifier=Eff+RiskMAP FW
Geom File=g01
Flow File=f02
Subcritical Flow
K Sum by GR= 0
Std Step Tol= 0.01
Critical Tol= 0.01
Num of Std Step Trials= 20
Max Error Tol= 0.3
Flow Tol Ratio= 0.001
Split Flow NTrial= 30
Split Flow Tol= 0.02
Split Flow Ratio= 0.02
Log Output Level= 0
Friction Slope Method= 1
Unsteady Friction Slope Method= 2
Unsteady Bridges Friction Slope Method= 1
Parabolic Critical Depth
Global Vel Dist= 0 , 0 , 0
Global Log Level= 0
CheckData=True
Encroach Param=-1 ,0,0, 2
Encroach River=C103-00-00
Encroach Reach=Reach - 1
Encroach Node=13585.7
       1  4973.9  5022.7
Encroach Node=13440.1
       1  4984.1  5022.7
Encroach Node=13430.9
       1    4975    5025
Encroach Node=13389.6
       1    4975    5025
Encroach Node=13348.3
       1    4975    5025
Encroach Node=13266.5
       1    4985    5025
Encroach Node=13141.3
       1    4980    5030
Encroach Node=13123.0
       1    4980    5030
Encroach Node=13076.7
       1    4980    5030
Encroach Node=13030.4
       1    4980    5030
Encroach Node=12878.4
       1    4970    5015
Encroach Node=12706.5
       1    4975    5015
Encroach Node=12679.2
       1    4970    5030
Encroach Node=12630.3
       1    4970    5030
Encroach Node=12581.4
       1    4970    5030
Encroach Node=12574.8
       1    4970    5030
Encroach Node=12420.6
       1    4970    5030
Encroach Node=11723.7
       1    4950    5050
Encroach Node=11024.0
       1    4900    5100
Encroach Node=10950.8
       1    4820    5150
Encroach Node=10890.2
       1    4820    5150
Encroach Node=10829.6
       1    4820    5150
Encroach Node=10772.3
       1    4840    5155
Encroach Node=10204.6
       1    4890    5155
Encroach Node=9530.4
       1    4930    5165
Encroach Node=9445.2
       1    4970    5200
Encroach Node=9137.7
       1    4970    5200
Encroach Node=8830.2
       1    4970    5200
Encroach Node=8760.0
       1    4970    5030
Encroach Node=8001.0
       1    4970    5070
Encroach Node=7058.1
       1    4970    5070
Encroach Node=7045.3
       1    4974    5070
Encroach Node=7009.1
       1    4974    5070
Encroach Node=6972.9
       1    4974    5070
Encroach Node=6933.2
       1  4946.5  5043.5
Encroach Node=6230.5
       1    4970    5033
Encroach Node=6118.6
       1  4973.3  5026.2
Encroach Node=5722.6
       1  4973.3  5026.2
Encroach Node=5326.6
       1  4973.3  5026.2
Encroach Node=5300.1
       1  4973.3  5026.2
Encroach Node=4873.2
       1  4976.2  5049.9
Encroach Node=4000.1
       1  4936.6  5073.3
Encroach Node=3857.7
       1  4936.6  5073.3
Encroach Node=3844.4
       1  4936.6  5073.3
Encroach Node=3831.1
       1  4936.6  5073.3
Encroach Node=3819.8
       1 4952.15 5080.95
Encroach Node=3808.0
       1 4952.15 5080.95
Encroach Node=3312.8
       1  4908.8  5042.3
Encroach Node=2527.3
       1  4932.7  5042.3
Encroach Node=1639.9
       1  4946.4  5034.9
Encroach Node=1520.7
       1  4946.4  5034.9
Encroach Node=1504.2
       1  4946.4  5034.9
Encroach Node=1487.7
       1  4946.4  5034.9
Encroach Node=1457.8
       1 4971.72 5026.72
Encroach Node=1420.2
       1 4971.72 5026.72
Encroach Node=1382.6
       1    4965    5032
Encroach Node=1379.7
       1    4965    5032
Encroach Node=1367.1
       1    4965    5032
Encroach Node=1085.8
       1    4870  5058.5
Encroach Node=701.9
       1    4870  5058.5
Encroach Reach=C103-00-00_0007
Encroach Node=13585.7
       1  4973.9  5022.7
Encroach Node=13440.1
       1  4984.1  5022.7
Encroach Node=13430.9
       1    4975    5025
Encroach Node=13389.6
       1    4975    5025
Encroach Node=13348.3
       1    4975    5025
Encroach Node=13266.5
       1    4985    5025
Encroach Node=13141.3
       1    4980    5030
Encroach Node=13123.0
       1    4980    5030
Encroach Node=13076.7
       1    4980    5030
Encroach Node=13030.4
       1    4980    5030
Encroach Node=12878.4
       1    4970    5015
Encroach Node=12706.5
       1    4975    5015
Encroach Node=12679.2
       1    4970    5030
Encroach Node=12630.3
       1    4970    5030
Encroach Node=12581.4
       1    4970    5030
Encroach Node=12574.8
       1    4970    5030
Encroach Node=12420.6
       1    4970    5030
Encroach Node=11723.7
       1    4950    5050
Encroach Node=11024.0
       1    4900    5100
Encroach Node=10950.8
       1    4820    5150
Encroach Node=10890.2
       1    4820    5150
Encroach Node=10829.6
       1    4820    5150
Encroach Node=10772.3
       1    4840    5155
Encroach Node=10204.6
       1    4890    5155
Encroach Node=9530.4
       1    4930    5165
Encroach Node=9445.2
       1    4970    5200
Encroach Node=9137.7
       1    4970    5200
Encroach Node=8830.2
       1    4970    5200
Encroach Node=8760.0
       1    4970    5030
Encroach Node=8001.0
       1    4970    5070
Encroach Node=7058.1
       1    4970    5070
Encroach Node=7045.3
       1    4974    5070
Encroach Node=7009.1
       1    4974    5070
Encroach Node=6972.9
       1    4974    5070
Encroach Node=6933.2
       1  4946.5  5043.5
Encroach Node=6230.5
       1    4970    5033
Encroach Node=6118.6
       1  4973.3  5026.2
Encroach Node=5722.6
       1  4973.3  5026.2
Encroach Node=5326.6
       1  4973.3  5026.2
Encroach Node=5300.1
       1  4973.3  5026.2
Encroach Node=4873.2
       1  4976.2  5049.9
Encroach Node=4000.1
       1  4936.6  5073.3
Encroach Node=3857.7
       1  4936.6  5073.3
Encroach Node=3844.4
       1  4936.6  5073.3
Encroach Node=3831.1
       1  4936.6  5073.3
Encroach Node=3819.8
       1 4952.15 5080.95
Encroach Node=3808.0
       1 4952.15 5080.95
Encroach Node=3312.8
       1  4908.8  5042.3
Encroach Node=2527.3
       1  4932.7  5042.3
Encroach Node=1639.9
       1  4946.4  5034.9
Encroach Node=1520.7
       1  4946.4  5034.9
Encroach Node=1504.2
       1  4946.4  5034.9
Encroach Node=1487.7
       1  4946.4  5034.9
Encroach Node=1457.8
       1 4971.72 5026.72
Encroach Node=1420.2
       1 4971.72 5026.72
Encroach Node=1382.6
       1    4965    5032
Encroach Node=1379.7
       1    4965    5032
Encroach Node=1367.1
       1    4965    5032
Encroach Node=1085.8
       1    4870  5058.5
Encroach Node=701.9
       1    4870  5058.5
BEGIN DESCRIPTION:
FEMA Effective Risk Map Study Floodway May 02, 2019
END DESCRIPTION:
Computation Interval=1HOUR
Output Interval=1HOUR
Run HTab= 0
Run UNet= 0
Run PostProcess= 0
Run WQNet= 0
UNET Theta= 1
UNET Theta Warmup= 1
UNET ZTol= 0.02
UNET ZSATol= 0.1
UNET MxIter= 20
UNET MaxInSteps= 20
UNET DtIC= 0
UNET DtMin= 0
UNET MaxCRTS= 20
UNET WFStab= 2
UNET SFStab= 1
UNET WFX= 1
UNET SFX= 1
UNET DSS MLevel= 4
UNET DZMax Abort= 100
UNET Convert EG Bridges=-1
UNET Use Existing IB Tables=-1
UNET Froude Reduction=False
UNET Froude Limit= 1
UNET Froude Power= 10
UNET Time Slicing=0,0, 5
UNET Junction Losses=0
Instantaneous Interval=1HOUR
Write IC File= 0
IC Time=0,,
Write IC File at Sim End=0
Echo Input=False
Echo Parameters=False
Echo Output=False
Write Detailed= 0
WQ AD Non Conservative
WQ ULTIMATE=-1
WQ Max Comp Step=1HOUR
WQ Output Interval=15MIN
WQ Output Selected Increments= 0
WQ Output face flow=0
WQ Output face velocity=0
WQ Output face area=0
WQ Output face dispersion=0
WQ Output cell volume=0
WQ Output cell surface area=0
WQ Output cell continuity=0
WQ Output cumulative cell continuity=0
WQ Output face conc=0
WQ Output face dconc_dx=0
WQ Output face courant=0
WQ Output face peclet=0
WQ Output face adv mass=0
WQ Output face disp mass=0
WQ Output cell mass=0
WQ Output cell source sink temp=0
WQ Output cell source sink nsm=0
WQ Output MaxMinRange=-1
WQ Daily Max Min Mean=-1
WQ Daily Range=0
WQ Daily Time=0
WQ Create Restart=0
WQ Fixed Restart=0
WQ System Summary=0
WQ Use Fixed Temperature=0
Sorting and Armoring Iterations= 10
XS Update Threshold= 0.02
Hydraulics Update Threshold= 0.02
Energy Slope Method= 1
Volume Change Method= 0
XS Weighting Method= 0
Number of US Weighted Cross Sections= 1
Number of DS Weighted Cross Sections= 1
Upstream XS Weight=0.25
Main XS Weight=0.5
Downstream XS Weight=0.25
Number of DS XS's Weighted with US Boundary= 1
Upstream Boundary Weight= 1
Weight of XSs Associated with US Boundary= 0
Number of US XS's Weighted with DS Boundary= 1
Downstream Boundary Weight= 0.5
Weight of XSs Associated with DS Boundary= 0.5
Sediment Output Level= 4
Mass or Volume Output= 0
Output Increment Type= 1
Profile and TS Output Increment= 10
XS Output Flag= 0
XS Output Increment= 10
Disregard all LS=0
Disregard all Conn=0
Disregard all Breaches=0
Disregard all Pumps=0

--- C103-00-00.p01 (plan) ---

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Plan Title=Effective Multi-Profile 2015
Short Identifier=Eff+RiskMAP MP
Geom File=g01
Flow File=f01
Encroach Param=-1 ,0,0, 0
FEMA Effective Risk Map Study Multi-Profile May 02, 2019
UNET ZSATol= 0.05
UNET MaxInSteps= 0

--- C103-00-00.f02 (steady flow) ---

Flow Title=Effective Floodway 2015
Program Version=4.10
Number of Profiles= 2
Profile Names=1PCT_100yr,Floodway
River Rch & RM=C103-00-00,C103-00-00_0007 ,13585.7
     412     412
River Rch & RM=C103-00-00,C103-00-00_0007 ,10890.2
     969     969
River Rch & RM=C103-00-00,C103-00-00_0007 ,4000.1
    1311    1311
River Rch & RM=C103-00-00,C103-00-00_0007 ,701.9
    2384    2384
Boundary for River Rch & Prof#=C103-00-00,C103-00-00_0007 , 1
Up Type= 0
Dn Type= 3
Dn Slope=0.0024
Boundary for River Rch & Prof#=C103-00-00,C103-00-00_0007 , 2
Up Type= 0
Dn Type= 1
Dn Known WS=10.51
DSS Import GetInterval= 0
DSS Import GetPeak= 0
DSS Import FillOption= 0

--- C103-00-00.f01 (steady flow) ---

Flow Title=Effective Multi-Profile 2015
Program Version=4.10
Number of Profiles= 6
Profile Names=10PCT_10yr,4PCT_25yr,2PCT_50yr,1PCT_100yr,1PCT_Plus,0.2PCT_500yr
River Rch & RM=C103-00-00,C103-00-00_0007 ,13585.7
     254     309     358     412     494     559
River Rch & RM=C103-00-00,C103-00-00_0007 ,10890.2
     597     726     841     969    1163    1313
River Rch & RM=C103-00-00,C103-00-00_0007 ,4000.1
     807     981    1137    1311    1573    1776
River Rch & RM=C103-00-00,C103-00-00_0007 ,701.9
    1468    1784    2068    2384    2861    3231
Boundary for River Rch & Prof#=C103-00-00,C103-00-00_0007 , 1
Up Type= 0
Dn Type= 3
Dn Slope=0.0024
Boundary for River Rch & Prof#=C103-00-00,C103-00-00_0007 , 2
Up Type= 0
Dn Type= 3
Dn Slope=0.0024
Boundary for River Rch & Prof#=C103-00-00,C103-00-00_0007 , 3
Up Type= 0
Dn Type= 3
Dn Slope=0.0024
Boundary for River Rch & Prof#=C103-00-00,C103-00-00_0007 , 4
Up Type= 0
Dn Type= 3
Dn Slope=0.0024
DSS Import GetInterval= 0
DSS Import GetPeak= 0
DSS Import FillOption= 0

--- C103-00-00.g01 (geometry) ---

Geom Title=C103-00-00 2015
Program Version=4.10

River Reach=C103-00-00      ,C103-00-00_0007
Reach XY= 30
      3143596.97     13816700.87       3143945.5       13816798.
        3144540.       13817239.      3146184.12     13817860.23
      3146695.08       13818346.        3147296.       13818667.
       3147744.1     13819118.01      3147852.92     13819101.27
        3148065.     13819257.54      3148048.25     13819360.78
      3148131.97     13819433.33      3148257.53     13819466.82
      3148826.25     13819367.16       3148967.4     13819271.68
      3149197.37     13819313.14      3149322.71     13819385.18
      3149360.21     13819720.75        3149740.       13819905.
        3150080.       13819923.      3150523.67     13819634.19
      3150938.81     13819739.97      3151340.48     13819688.16
        3151814.       13819741.      3152507.36     13819223.56
      3152814.28     13819162.66      3153439.34     13819288.23
        3153626.       13819423.        3153856.       13819473.
      3154381.05      13819828.5      3154463.81     13819994.02

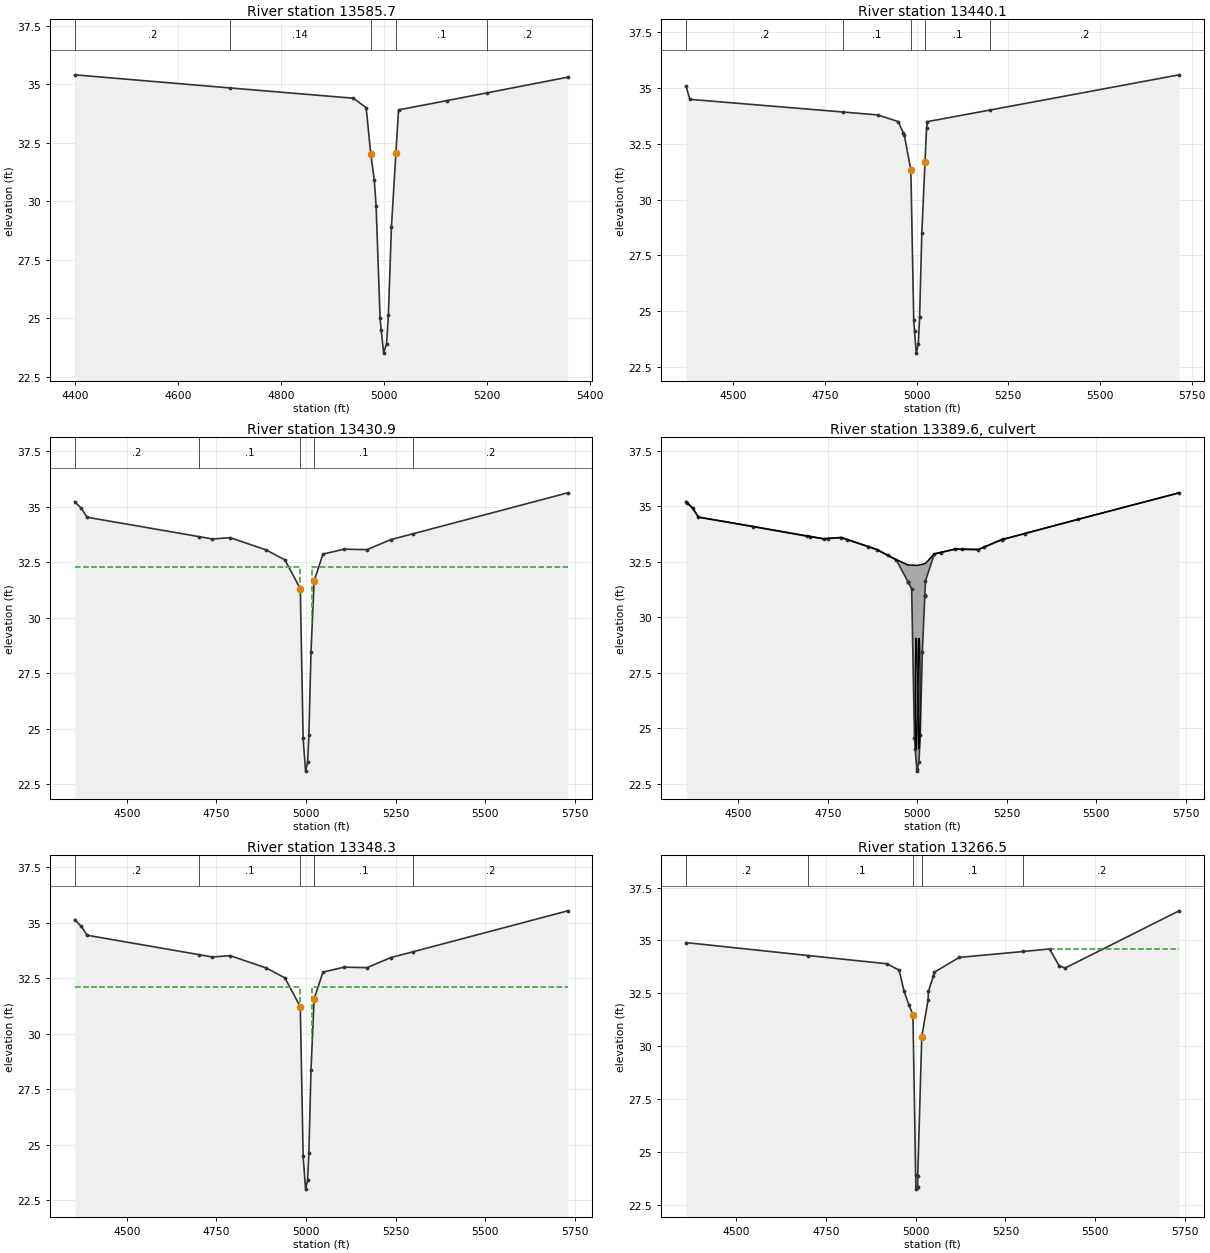
Type RM Length L Ch R = 1 ,13585.7 ,146.6,145.6,145
BEGIN DESCRIPTION:
Cross Section 13585.7-Interpolated
END DESCRIPTION:
XS GIS Cut Line= 4
       3143428.5     13817278.29      3143579.01      13816758.4
        3143611.     13816656.03      3143706.97     13816361.71
#Sta/Elev= 18
  4398.5    35.4    4700   34.84  4939.7    34.4  4964.9      34  4973.9      32
  4980.7    30.9  4984.2    29.8    4992   24.99  4994.1    24.5  4998.8    23.5
  5004.5    23.9    5008   25.11    5014   28.89  5022.7   32.07  5027.8    33.9
  5122.4    34.3    5200   34.63  5356.6    35.3
#Mann= 5 , 1 , 0
  4398.5      .2       0    4700     .14       0  4973.9     .04       0
  5022.7      .1       0    5200      .2       0
Bank Sta=4973.9,5022.7
XS Rating Curve= 0 ,0
Exp/Cntr=0.3,0.1

Type RM Length L Ch R = 1 ,13440.1 ,10,9.2,8
BEGIN DESCRIPTION:
Cross Section 13440.1-Interpolated
END DESCRIPTION:
XS GIS Cut Line= 4
      3143498.62      13817316.7      3143679.49      13816826.2
      3143739.67     13816688.14      3144006.11     13816071.75
#Sta/Elev= 19
  4370.9    35.1  4381.2    34.5    4800   33.93  4894.2    33.8  4949.8    33.5
  4963.4      33  4966.2    32.9  4984.1   31.33    4992    24.6  4994.1   24.11
  4998.8   23.11  5004.5   23.51    5008   24.72    5014    28.5  5022.7   31.68
  5026.9    33.2  5029.5    33.5    5200   34.02  5715.8    35.6
#Mann= 5 , 1 , 0
  4370.9      .2       0    4800      .1       0  4984.1     .04       0
  5022.7      .1       0    5200      .2       0
Bank Sta=4984.1,5022.7
XS Rating Curve= 0 ,0
Exp/Cntr=0.5,0.3

Type RM Length L Ch R = 1 ,13430.9 ,82.6,82.6,82.6
BEGIN DESCRIPTION:
Upstream Section of Bridge/Culvert/Weir
END DESCRIPTION:
XS GIS Cut Line= 6
      3143577.27       13817353.      3143695.68      13817044.4
      3143733.01     13816795.89      3143773.73     13816659.48
      3143942.69     13816357.73      3144040.31     13816068.23
#Sta/Elev= 21
  4354.2   35.23  4372.7   34.93  4388.9   34.53    4700   33.66  4738.7   33.55
  4788.2   33.61  4888.3   33.06    4941   32.61  4984.1   31.31    4992   24.58
  4998.8   23.09  5004.5   23.49    5008    24.7    5014   28.48  5022.7   31.66
  5047.3   32.87  5106.1   33.09  5170.6   33.07  5236.2   33.52    5300   33.79
  5730.8   35.63
#Mann= 5 , 1 , 0
  4354.2      .2       0    4700      .1       0  4984.1     .04       0
  5022.7      .1       0    5300      .2       0
#XS Ineff= 2 , 0
       0  4984.4    32.3  5017.4       0    32.3
Permanent Ineff=
       F       F
Bank Sta=4984.1,5022.7
XS Rating Curve= 0 ,0
Exp/Cntr=0.5,0.3

Type RM Length L Ch R = 2 ,13389.6 ,,,
BEGIN DESCRIPTION:
PLUM DRIVE
Structure ID: C03-10
END DESCRIPTION:
Bridge Culvert--1,0,-1,-1, 0
Deck Dist Width WeirC Skew NumUp NumDn MinLoCord MaxHiCord MaxSubmerge Is_Ogee
10,62.6,3,0, 41, 41, , , 0.95, 0, 1,1,,
  4354.2  4356.5  4372.7  4388.9  4539.8  4690.8    4700  4738.7  4751.7  4788.2
  4804.3  4863.3  4888.3    4917    4941 4973.79  4973.9 4974.01  4984.1    4992
  4994.1  4998.8    5000  5004.5    5008    5014 5020.79  5020.9 5021.01  5022.7
  5047.3  5065.5  5106.1  5125.3  5170.6    5185  5236.2  5239.7    5300  5448.7
  5730.8
    35.2   35.17   34.91   34.51   34.09   33.66   33.64   33.53   33.55   33.59
    33.5   33.18   33.04   32.79   32.59   32.35   32.35   32.35   32.34   32.34
   32.33   32.33   32.33   32.35   32.36   32.38   32.41   32.41   32.41   32.42
   32.85   32.92   33.07   33.06   33.05   33.15    33.5   33.51   33.77   34.41
    35.6
    35.2   35.16    34.9    34.5   34.08   33.65   33.63   33.52   33.54   33.58
   33.49   33.17   33.03   32.78   32.58   31.59   31.59   31.58   31.28   24.55
   24.06   23.06   23.14   23.46   24.67   28.45   30.93   30.97   31.01   31.63
   32.84   32.91   33.06   33.05   33.04   33.14   33.49    33.5   33.76    34.4
    35.6
  4354.2  4356.5  4372.7  4388.9  4539.8  4690.8    4700  4738.7  4751.7  4788.2
  4804.3  4863.3  4888.3    4917    4941 4973.79  4973.9 4974.01  4984.1    4992
  4994.1  4998.8    5000  5004.5    5008    5014 5020.79  5020.9 5021.01  5022.7
  5047.3  5065.5  5106.1  5125.3  5170.6    5185  5236.2  5239.7    5300  5448.7
  5730.8
    35.2   35.17   34.91   34.51   34.09   33.66   33.64   33.53   33.55   33.59
    33.5   33.18   33.04   32.79   32.59   32.35   32.35   32.35   32.34   32.34
   32.33   32.33   32.33   32.35   32.36   32.38   32.41   32.41   32.41   32.42
   32.85   32.92   33.07   33.06   33.05   33.15    33.5   33.51   33.77   34.41
    35.6
    35.1   35.06    34.8    34.4   33.98   33.55   33.53   33.42   33.44   33.48
   33.39   33.07   32.93   32.68   32.48   31.49   31.49   31.48   31.18   24.45
   23.96   22.96   23.04   23.36   24.57   28.35   30.83   30.87   30.91   31.53
   32.74   32.81   32.96   32.95   32.94   33.04   33.39    33.4   33.66    34.3
    35.5
BR Coef= 1 , 0 , 0 ,1.25, 0 ,,,0.8,-1,2,0,
WSPro=,,,, 1 ,,,, 0 ,,,, 0 ,,,,-1 ,-1 ,-1 , 0 , 0 , 0 , 0 , 0
Culvert=1,5,,62.6,0.015,0.5,1,1,3,24.06,4996.9,23.88,4996.9,Culvert #1  , 0 ,10
Culvert Bottom n=0.015
Culvert=1,5,,62.6,0.015,0.5,1,1,3,24.06,5004.9,23.88,5004.9,Culvert #2  , 0 ,10
Culvert Bottom n=0.015
BR U #Sta/Elev= 41
  4354.2    35.2  4356.5   35.16  4372.7    34.9  4388.9    34.5  4539.8   34.08
  4690.8   33.65    4700   33.63  4738.7   33.52  4751.7   33.54  4788.2   33.58
  4804.3   33.49  4863.3   33.17  4888.3   33.03    4917   32.78    4941   32.58
 4973.79   31.59  4973.9   31.59 4974.01   31.58  4984.1   31.28    4992   24.55
  4994.1   24.06  4998.8   23.06    5000   23.14  5004.5   23.46    5008   24.67
    5014   28.45 5020.79   30.93  5020.9   30.97 5021.01   31.01  5022.7   31.63
  5047.3   32.84  5065.5   32.91  5106.1   33.06  5125.3   33.05  5170.6   33.04
    5185   33.14  5236.2   33.49  5239.7    33.5    5300   33.76  5448.7    34.4
  5730.8    35.6
BR U #Mann= 5
  4354.2      .2    4700      .1  4984.1     .04  5022.7      .1    5300      .2
BR U Banks=4984.1,5022.7
BR D #Sta/Elev= 41
  4354.2    35.1  4356.5   35.06  4372.7    34.8  4388.9    34.4  4539.8   33.98
  4690.8   33.55    4700   33.53  4738.7   33.42  4751.7   33.44  4788.2   33.48
  4804.3   33.39  4863.3   33.07  4888.3   32.93    4917   32.68    4941   32.48
 4973.79   31.49  4973.9   31.49 4974.01   31.48  4984.1   31.18    4992   24.45
  4994.1   23.96  4998.8   22.96    5000   23.04  5004.5   23.36    5008   24.57
    5014   28.35 5020.79   30.83  5020.9   30.87 5021.01   30.91  5022.7   31.53
  5047.3   32.74  5065.5   32.81  5106.1   32.96  5125.3   32.95  5170.6   32.94
    5185   33.04  5236.2   33.39  5239.7    33.4    5300   33.66  5448.7    34.3
  5730.8    35.5
BR D #Mann= 5
  4354.2      .2    4700      .1  4984.1     .04  5022.7      .1    5300      .2
BR D Banks=4984.1,5022.7
BC Design=,, 0 ,, 0 ,,,,,,
BC HTab HWMax=35.63
BC Use User HTab Curves=0
BC User HTab FreeFlow(D)= 0

Type RM Length L Ch R = 1 ,13348.3 ,81.8,81.8,81.8
BEGIN DESCRIPTION:
Downstream Section of Bridge/Culvert/Weir
END DESCRIPTION:
XS GIS Cut Line= 6
      3143658.16     13817369.72      3143776.58     13817061.12
      3143813.91     13816812.61      3143854.63      13816676.2
      3144023.59     13816374.45       3144121.2     13816084.95
#Sta/Elev= 21
  4354.2   35.13  4372.7   34.83  4388.9   34.43    4700   33.56  4738.7   33.45
  4788.2   33.51  4888.3   32.96    4941   32.51  4984.1   31.21    4992   24.48
  4998.8   22.99  5004.5   23.39    5008    24.6    5014   28.38  5022.7   31.56
  5047.3   32.77  5106.1   32.99  5170.6   32.97  5236.2   33.42    5300   33.69
  5730.8   35.53
#Mann= 5 , 1 , 0
  4354.2      .2       0    4700      .1       0  4984.1     .04       0
  5022.7      .1       0    5300      .2       0
#XS Ineff= 2 , 0
       0  4984.4    32.1  5017.4       0    32.1
Permanent Ineff=
       F       F
Bank Sta=4984.1,5022.7
XS Rating Curve= 0 ,0
Exp/Cntr=0.5,0.3

Type RM Length L Ch R = 1 ,13266.5 ,219.6,125.2,113.2
BEGIN DESCRIPTION:
Cross Section 13266.5
END DESCRIPTION:
XS GIS Cut Line= 6
      3143713.12     13817391.49      3143873.23     13816855.16
      3143904.75     13816782.02      3143924.13     13816737.07
      3143962.81     13816675.98      3144200.96      13816111.9
#Sta/Elev= 23
  4360.7    34.9    4700   34.29  4920.4    33.9    4954    33.6  4967.6   32.62
  4981.6   31.94  4992.5    31.5    5000   23.94  5000.7   23.26  5003.7    23.3
  5005.6   23.38  5005.8   23.86  5017.1   30.46  5034.7    32.2  5035.6    32.6
    5049    33.3  5051.8    33.5  5121.3    34.2    5300   34.48  5372.8    34.6
  5399.9    33.8  5416.2    33.7  5733.6    36.4
#Mann= 5 , 1 , 0
  4360.7      .2       0    4700      .1       0  4992.5     .04       0
  5017.1      .1       0    5300      .2       0
#XS Ineff= 2 , 0
       0                  5371.3       0   34.61
Permanent Ineff=
       F       F
Bank Sta=4992.5,5017.1
XS Rating Curve= 0 ,0
Exp/Cntr=0.3,0.1

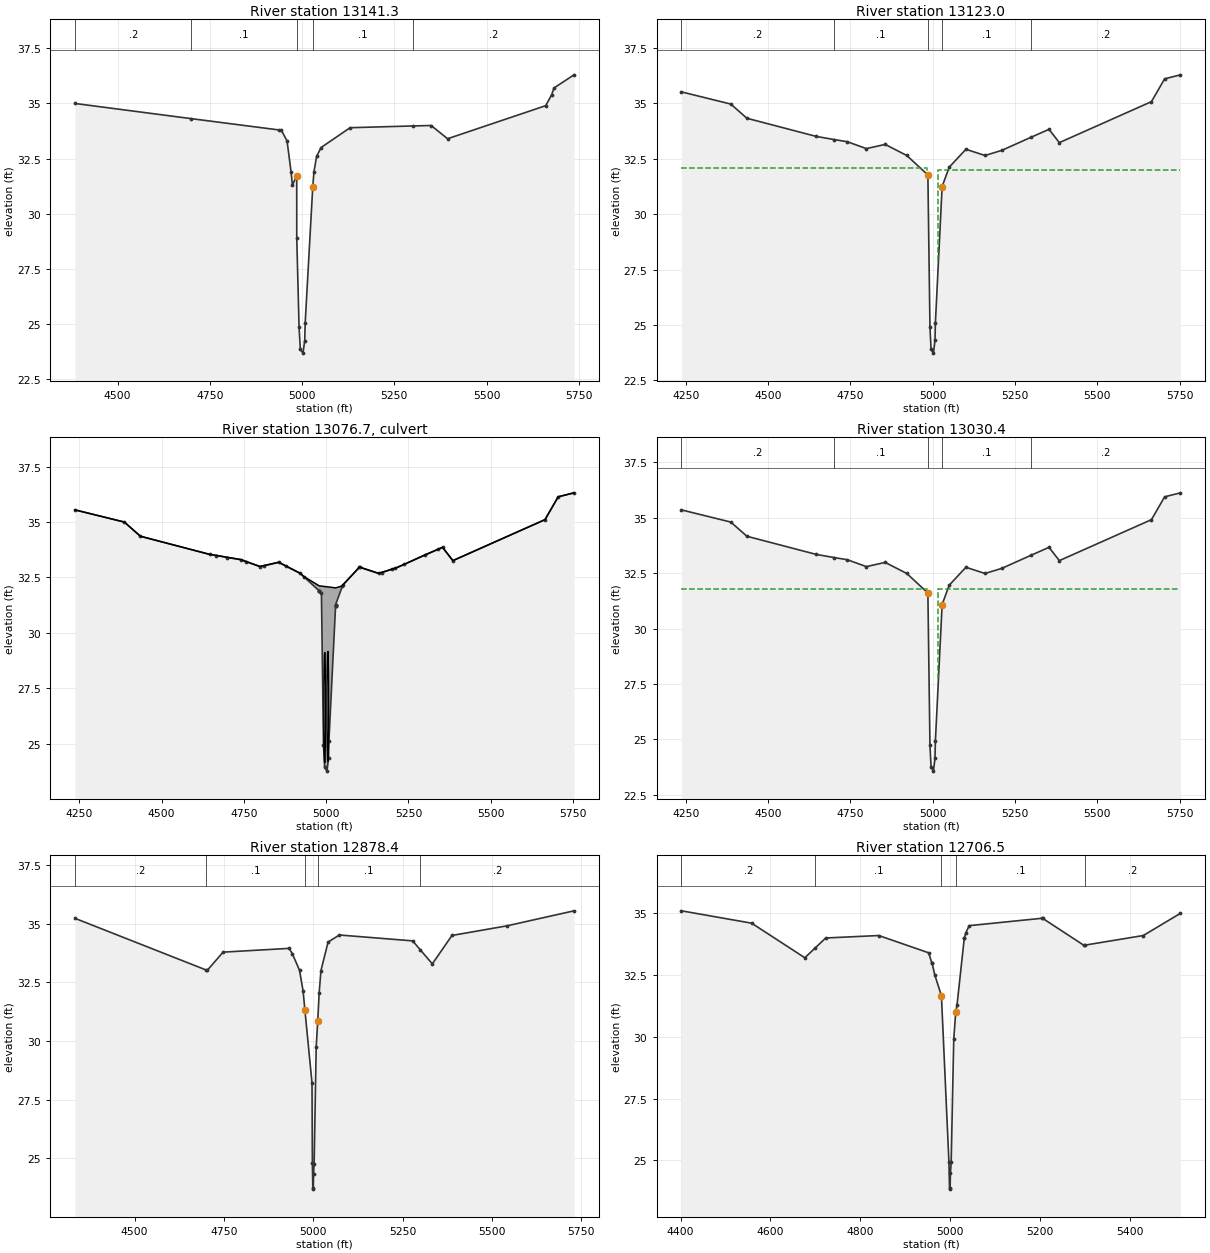
Type RM Length L Ch R = 1 ,13141.3 ,21,18.3,14
BEGIN DESCRIPTION:
Cross Section 13141.3-Interpolated
END DESCRIPTION:
XS GIS Cut Line= 5
      3143745.46     13817401.19      3143988.85     13816905.53
      3144029.29     13816798.13       3144080.1       13816681.
      3144301.75     13816168.94
#Sta/Elev= 26
  4384.3      35    4700   34.31  4936.5    33.8  4943.1    33.8  4959.1    33.3
    4970    31.9  4973.7    31.3  4985.3   31.71  4985.4    28.9  4991.7   24.85
  4995.1   23.84  5002.3   23.67    5007   24.24  5008.2   25.03  5028.7   31.19
    5032    31.9  5039.3    32.6  5051.3      33    5130    33.9    5300   33.98
  5349.6      34  5394.3    33.4  5660.2    34.9  5676.5    35.4  5682.5    35.7
  5736.9    36.3
#Mann= 5 , 1 , 0
  4384.3      .2       0    4700      .1       0  4985.3     .04       0
  5028.7      .1       0    5300      .2       0
Bank Sta=4985.3,5028.7
XS Rating Curve= 0 ,0
Exp/Cntr=0.5,0.3

Type RM Length L Ch R = 1 ,13123.0 ,92.6,92.6,92.6
BEGIN DESCRIPTION:
Upstream Section of Bridge/Culvert/Weir
END DESCRIPTION:
XS GIS Cut Line= 6
      3143680.99     13817505.54      3143964.28     13817188.26
      3144056.32     13816766.99      3144123.58     13816653.71
       3144258.1     13816515.65      3144394.14     13816212.95
#Sta/Elev= 26
  4236.6   35.52  4386.6   34.97  4435.4   34.33  4646.3   33.51    4700   33.37
  4740.7   33.27  4798.4   32.96  4855.6   33.15  4921.3   32.65  4985.4   31.77
  4991.7   24.91  4995.1    23.9  5002.3   23.73    5007    24.3  5008.2   25.09
  5028.7   31.25  5050.1   32.12    5101   32.93    5159   32.65  5209.8   32.88
    5300   33.48  5353.5   33.83  5384.8   33.23  5664.8   35.08  5704.8   36.11
  5752.9   36.29
#Mann= 5 , 1 , 0
  4236.6      .2       0    4700      .1       0  4985.4     .04       0
  5028.7      .1       0    5300      .2       0
#XS Ineff= 2 , 0
       0  4983.1    32.1  5017.5       0      32
Permanent Ineff=
       F       F
Bank Sta=4985.4,5028.7
XS Rating Curve= 0 ,0
Exp/Cntr=0.5,0.3

Type RM Length L Ch R = 2 ,13076.7 ,,,
BEGIN DESCRIPTION:
IRVING DRIVE
Structure ID: C03-9
END DESCRIPTION:
Bridge Culvert--1,0,-1,-1, 0
Deck Dist Width WeirC Skew NumUp NumDn MinLoCord MaxHiCord MaxSubmerge Is_Ogee
10,72.6,3,0, 44, 44, , , 0.95, 0, 1,1,,
  4236.6  4386.6  4435.4  4646.3  4665.9    4700  4740.7  4755.3  4798.4  4811.8
  4855.6    4879  4921.3  4932.2 4978.89    4979 4979.11  4985.4  4991.7  4991.8
  4995.1  5002.3    5007  5008.2 5028.39  5028.5 5028.61  5028.7  5049.2  5050.1
    5101  5101.3    5159  5168.7    5200  5209.8  5237.5    5300  5340.5  5353.5
  5384.8  5664.8  5704.8  5752.9
   35.55      35   34.36   33.54    33.5   33.41   33.31   33.23      33   33.04
   33.19   33.01   32.69   32.54   32.12   32.12   32.12   32.11    32.1    32.1
   32.09   32.08   32.07   32.07   32.03   32.03   32.03   32.03   32.12   32.16
   32.97   32.97   32.69   32.73   32.88   32.92    33.1   33.52   33.78   33.86
   33.26   35.11   36.14   36.32
   35.55      35   34.36   33.54   33.49    33.4    33.3   33.22   32.99   33.03
   33.18      33   32.68   32.53   31.89   31.89   31.89    31.8   24.94   24.91
   23.93   23.76   24.33   25.12   31.19   31.22   31.25   31.28   32.11   32.15
   32.96   32.96   32.68   32.72   32.87   32.91   33.09   33.51   33.77   33.86
   33.26   35.11   36.14   36.32
  4236.6  4386.6  4435.4  4646.3  4665.9    4700  4740.7  4755.3  4798.4  4811.8
  4855.6    4879  4921.3  4932.2 4978.89    4979 4979.11  4985.4  4991.7  4991.8
  4995.1  5002.3    5007  5008.2 5028.39  5028.5 5028.61  5028.7  5049.2  5050.1
    5101  5101.3    5159  5168.7    5200  5209.8  5237.5    5300  5340.5  5353.5
  5384.8  5664.8  5704.8  5752.9
   35.55      35   34.36   33.54    33.5   33.41   33.31   33.23      33   33.04
   33.19   33.01   32.69   32.54   32.12   32.12   32.12   32.11    32.1    32.1
   32.09   32.08   32.07   32.07   32.03   32.03   32.03   32.03   32.12   32.16
   32.97   32.97   32.69   32.73   32.88   32.92    33.1   33.52   33.78   33.86
   33.26   35.11   36.14   36.32
   35.35    34.8   34.16   33.34   33.29    33.2    33.1   33.02   32.79   32.83
   32.98    32.8   32.48   32.33   31.69   31.69   31.69    31.6   24.74   24.71
   23.73   23.56   24.13   24.92   30.99   31.02   31.05   31.08   31.91   31.95
   32.76   32.76   32.48   32.52   32.67   32.71   32.89   33.31   33.57   33.66
   33.06   34.91   35.94   36.12
BR Coef= 1 , 0 , 0 ,1.25, 0 ,,,0.8,-1,2,0,
WSPro=,,,, 1 ,,,, 0 ,,,, 0 ,,,,-1 ,-1 ,-1 , 0 , 0 , 0 , 0 , 0
Culvert=1,5,,72.6,0.015,0.4,1,1,3,24.13,4995.5,24.04,4995.5,Culvert #1  , 0 ,10
Culvert Bottom n=0.015
Culvert=1,5,,72.6,0.015,0.4,1,1,3,24.18,5004.9,24.06,5004.9,Culvert #2  , 0 ,10
Culvert Bottom n=0.015
BR U #Sta/Elev= 44
  4236.6   35.55  4386.6      35  4435.4   34.36  4646.3   33.54  4665.9   33.49
    4700    33.4  4740.7    33.3  4755.3   33.22  4798.4   32.99  4811.8   33.03
  4855.6   33.18    4879      33  4921.3   32.68  4932.2   32.53 4978.89   31.89
    4979   31.89 4979.11   31.89  4985.4    31.8  4991.7   24.94  4991.8   24.91
  4995.1   23.93  5002.3   23.76    5007   24.33  5008.2   25.12 5028.39   31.19
  5028.5   31.22 5028.61   31.25  5028.7   31.28  5049.2   32.11  5050.1   32.15
    5101   32.96  5101.3   32.96    5159   32.68  5168.7   32.72    5200   32.87
  5209.8   32.91  5237.5   33.09    5300   33.51  5340.5   33.77  5353.5   33.86
  5384.8   33.26  5664.8   35.11  5704.8   36.14  5752.9   36.32
BR U #Mann= 5
  4236.6      .2    4700      .1  4985.4     .04  5028.7      .1    5300      .2
BR U Banks=4985.4,5028.7
BR D #Sta/Elev= 44
  4236.6   35.35  4386.6    34.8  4435.4   34.16  4646.3   33.34  4665.9   33.29
    4700    33.2  4740.7    33.1  4755.3   33.02  4798.4   32.79  4811.8   32.83
  4855.6   32.98    4879    32.8  4921.3   32.48  4932.2   32.33 4978.89   31.69
    4979   31.69 4979.11   31.69  4985.4    31.6  4991.7   24.74  4991.8   24.71
  4995.1   23.73  5002.3   23.56    5007   24.13  5008.2   24.92 5028.39   30.99
  5028.5   31.02 5028.61   31.05  5028.7   31.08  5049.2   31.91  5050.1   31.95
    5101   32.76  5101.3   32.76    5159   32.48  5168.7   32.52    5200   32.67
  5209.8   32.71  5237.5   32.89    5300   33.31  5340.5   33.57  5353.5   33.66
  5384.8   33.06  5664.8   34.91  5704.8   35.94  5752.9   36.12
BR D #Mann= 5
  4236.6      .2    4700      .1  4985.4     .04  5028.7      .1    5300      .2
BR D Banks=4985.4,5028.7
BC Design=,, 0 ,, 0 ,,,,,,
BC HTab HWMax=36.29
BC Use User HTab Curves=0
BC User HTab FreeFlow(D)= 0

Type RM Length L Ch R = 1 ,13030.4 ,152,152,152
BEGIN DESCRIPTION:
Downstream Section of Bridge/Culvert/Weir
END DESCRIPTION:
XS GIS Cut Line= 6
      3143755.71     13817560.23        3144039.     13817242.96
      3144131.04     13816821.69       3144198.3     13816708.41
      3144332.82     13816570.35      3144468.86     13816267.64
#Sta/Elev= 26
  4236.6   35.36  4386.6   34.81  4435.4   34.17  4646.3   33.35    4700   33.21
  4740.7   33.11  4798.4    32.8  4855.6   32.99  4921.3   32.49  4985.4   31.61
  4991.7   24.75  4995.1   23.74  5002.3   23.57    5007   24.14  5008.2   24.93
  5028.7   31.09  5050.1   31.96    5101   32.77    5159   32.49  5209.8   32.72
    5300   33.32  5353.5   33.67  5384.8   33.07  5664.8   34.92  5704.8   35.95
  5752.9   36.13
#Mann= 5 , 1 , 0
  4236.6      .2       0    4700      .1       0  4985.4     .04       0
  5028.7      .1       0    5300      .2       0
#XS Ineff= 2 , 0
       0  4983.1    31.8  5017.5       0    31.8
Permanent Ineff=
       F       F
Bank Sta=4985.4,5028.7
XS Rating Curve= 0 ,0
Exp/Cntr=0.5,0.3

Type RM Length L Ch R = 1 ,12878.4 ,90.6,171.9,267.3
BEGIN DESCRIPTION:
Cross Section 12878.4-Interpolated
END DESCRIPTION:
XS GIS Cut Line= 6
      3143801.89     13817528.83      3144075.34      13817217.4
      3144185.49     13817057.88      3144257.65     13816947.74
      3144527.31     13816564.14      3144595.67     13816389.43
#Sta/Elev= 27
  4333.2   35.23    4700   33.03  4703.2   33.01  4747.7   33.79  4932.7   33.95
  4941.5   33.72  4961.5   33.02  4971.5   32.14  4976.5   31.34  4996.5   28.22
  4997.5   24.79  4998.8   23.73  5000.1   23.69  5000.8   24.33  5002.5   24.77
  5008.2   29.75  5012.6   30.86  5016.5   32.05  5021.5      33  5041.5   34.22
  5073.2   34.52  5278.2   34.27    5300   33.88  5333.2   33.29  5388.2    34.5
  5542.1   34.91  5729.7   35.55
#Mann= 5 , 1 , 0
  4333.2      .2       0    4700      .1       0  4976.5     .04       0
  5012.6      .1       0    5300      .2       0
#XS Ineff= 2 , 0
       0                  5278.2       0   34.27
Permanent Ineff=
       F       F
Bank Sta=4976.5,5012.6
XS Rating Curve= 0 ,0
Exp/Cntr=0.3,0.1

Type RM Length L Ch R = 1 ,12706.5 ,32,27.3,26.9
BEGIN DESCRIPTION:
Cross Section 12706.5-Interpolated
END DESCRIPTION:
XS GIS Cut Line= 6
      3143903.94     13817485.28       3144088.7     13817222.69
      3144309.38     13817139.57      3144378.17     13817108.04
      3144495.81     13816983.97      3144618.71     13816702.59
#Sta/Elev= 29
  4402.1    35.1  4558.3    34.6  4676.7    33.2    4700    33.6  4723.2      34
  4841.3    34.1  4952.4    33.4  4959.2      33  4959.7      33  4966.1    32.5
  4980.8   31.66  4997.5   24.93  4998.8   23.87  5000.1   23.83  5000.8   24.47
  5002.5   24.91  5008.2   29.89  5012.6      31  5015.6    31.3  5031.7      34
    5032      34  5034.8    34.2  5042.7    34.5  5205.6    34.8  5205.8    34.8
  5298.2    33.7    5300   33.71  5430.2    34.1  5512.9      35
#Mann= 5 , 1 , 0
  4402.1      .2       0    4700      .1       0  4980.8     .04       0
  5012.6      .1       0    5300      .2       0
#XS Ineff= 2 , 0
       0                  5205.8       0    34.8
Permanent Ineff=
       F       F
Bank Sta=4980.8,5012.6
XS Rating Curve= 0 ,0
Exp/Cntr=0.5,0.3

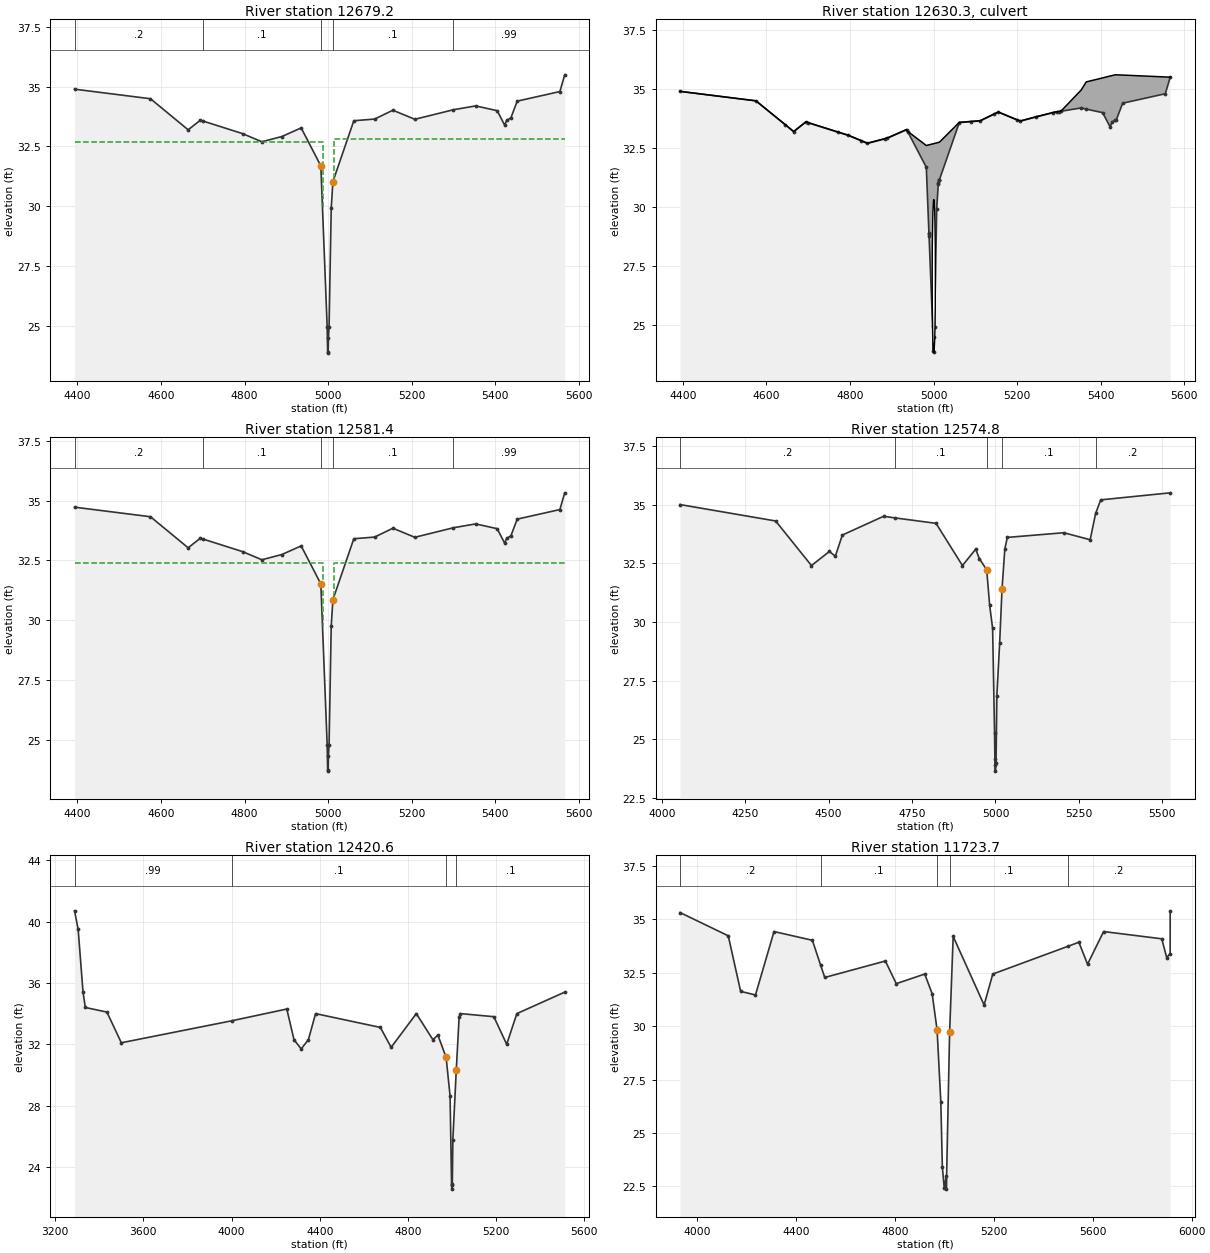
Type RM Length L Ch R = 1 ,12679.2 ,97.8,97.8,97.8
BEGIN DESCRIPTION:
Upstream Section of Bridge/Culvert/Weir
END DESCRIPTION:
XS GIS Cut Line= 6
      3143909.02     13817508.57      3144092.12     13817287.33
      3144228.81     13817200.34      3144368.65     13817145.25
      3144460.28     13817074.92      3144794.74     13816762.49
#Sta/Elev= 30
  4393.2   34.89  4574.9   34.49  4665.1   33.19  4694.1   33.59    4700   33.56
 4795.43   33.03 4841.45   32.69 4889.38   32.91 4935.49   33.27  4982.6   31.68
 4997.74   24.95 4998.91   23.89 5000.09   23.85 5000.72   24.49 5002.27   24.93
 5007.43   29.91 5011.42   31.02 5061.52   33.57 5111.53   33.64 5155.02   34.01
 5207.47   33.63    5300   34.03  5353.3   34.19  5404.6   33.99  5422.3   33.39
  5427.5   33.59  5437.4   33.69  5452.5   34.39  5554.6   34.79  5566.2   35.49
#Mann= 5 , 1 , 0
  4393.2      .2       0    4700      .1       0  4982.6     .04       0
 5011.42      .1       0    5300     .99       0
#XS Ineff= 2 , 0
       0  4986.7    32.7    5014       0    32.8
Permanent Ineff=
       F       F
Bank Sta=4982.6,5011.42
XS Rating Curve= 0 ,0
Exp/Cntr=0.5,0.3

Type RM Length L Ch R = 2 ,12630.3 ,,,
BEGIN DESCRIPTION:
FAIRWAY DRIVE, SKEW ANGLE OF 25 DEGREES
Structure ID: C03-8
END DESCRIPTION:
Bridge Culvert--1,0,-1,-1, 0
Deck Dist Width WeirC Skew NumUp NumDn MinLoCord MaxHiCord MaxSubmerge Is_Ogee
10,77.8,3,0, 51, 51, , , 0.95, 0, 1,1,,
  4393.2  4574.9  4644.8  4665.1  4694.1    4700  4771.8 4795.43  4825.6 4841.45
  4883.1 4889.38 4935.49  4937.9  4982.6 4988.89    4989 4989.11 4997.74 4998.91
 5000.09 5000.72 5002.27 5007.43  5011.2 5011.42 5013.69  5013.8 5013.91 5061.52
  5089.2 5111.53  5144.1 5155.02    5200 5207.47  5245.8  5286.3  5295.2    5300
  5305.2  5353.3  5365.2  5404.6  5422.3  5427.5  5434.2  5437.4  5452.5  5554.6
  5566.2
    34.9    34.5    33.5    33.2   33.61   33.58   33.18   33.05   32.83   32.71
    32.9   32.93   33.29   33.21   32.61   32.64   32.64   32.64   32.68   32.68
   32.69   32.69    32.7   32.72   32.74   32.74   32.75   32.75   32.75   33.59
   33.63   33.66   33.94   34.03    33.7   33.65   33.83   34.01   34.04   34.05
   34.07   34.96    35.3   35.47   35.55   35.57    35.6    35.6   35.59   35.51
    35.5
    34.9    34.5   33.49    33.2    33.6   33.57   33.17   33.04   32.82    32.7
   32.89   32.92   33.28    33.2   31.69   28.89   28.85    28.8   24.96    23.9
   23.86    24.5   24.94   29.92   30.97   31.03   31.15   31.15   31.16   33.58
   33.62   33.65   33.93   34.02   33.69   33.64   33.82      34   34.03   34.04
   34.06    34.2   34.15      34    33.4    33.6   33.67    33.7    34.4    34.8
    35.5
  4393.2  4574.9  4644.8  4665.1  4694.1    4700  4771.8 4795.43  4825.6 4841.45
  4883.1 4889.38 4935.49  4937.9  4982.6 4988.89    4989 4989.11 4997.74 4998.91
 5000.09 5000.72 5002.27 5007.43  5011.2 5011.42 5013.69  5013.8 5013.91 5061.52
  5089.2 5111.53  5144.1 5155.02    5200 5207.47  5245.8  5286.3  5295.2    5300
  5305.2  5353.3  5365.2  5404.6  5422.3  5427.5  5434.2  5437.4  5452.5  5554.6
  5566.2
    34.9    34.5    33.5    33.2   33.61   33.58   33.18   33.05   32.83   32.71
    32.9   32.93   33.29   33.21   32.61   32.64   32.64   32.64   32.68   32.68
   32.69   32.69    32.7   32.72   32.74   32.74   32.75   32.75   32.75   33.59
   33.63   33.66   33.94   34.03    33.7   33.65   33.83   34.01   34.04   34.05
   34.07   34.96    35.3   35.47   35.55   35.57    35.6    35.6   35.59   35.51
    35.5
    34.8    34.4   33.39    33.1    33.5   33.47   33.07   32.94   32.72    32.6
   32.79   32.82   33.18    33.1   31.59   28.79   28.75    28.7   24.86    23.8
   23.76    24.4   24.84   29.82   30.87   30.93   31.05   31.05   31.06   33.48
   33.52   33.55   33.83   33.92   33.59   33.54   33.72    33.9   33.93   33.94
   33.96    34.1   34.05    33.9    33.3    33.5   33.57    33.6    34.3    34.7
    35.4
BR Coef= 1 , 0 , 0 ,1.25, 0 ,,,0.8,-1,2,0,
WSPro=,,,, 1 ,,,, 0 ,,,, 0 ,,,,-1 ,-1 ,-1 , 0 , 0 , 0 , 0 , 0
Culvert=4,6.5,7.5,77.8,0.024,0.7,1,29,1,23.83,5000.5,23.73,5000.5,Culvert #1  , 0 ,10
Culvert Bottom n=0.024
BR U #Sta/Elev= 51
  4393.2    34.9  4574.9    34.5  4644.8   33.49  4665.1    33.2  4694.1    33.6
    4700   33.57  4771.8   33.17 4795.43   33.04  4825.6   32.82 4841.45    32.7
  4883.1   32.89 4889.38   32.92 4935.49   33.28  4937.9    33.2  4982.6   31.69
 4988.89   28.89    4989   28.85 4989.11    28.8 4997.74   24.96 4998.91    23.9
 5000.09   23.86 5000.72    24.5 5002.27   24.94 5007.43   29.92  5011.2   30.97
 5011.42   31.03 5013.69   31.15  5013.8   31.15 5013.91   31.16 5061.52   33.58
  5089.2   33.62 5111.53   33.65  5144.1   33.93 5155.02   34.02    5200   33.69
 5207.47   33.64  5245.8   33.82  5286.3      34  5295.2   34.03    5300   34.04
  5305.2   34.06  5353.3    34.2  5365.2   34.15  5404.6      34  5422.3    33.4
  5427.5    33.6  5434.2   33.67  5437.4    33.7  5452.5    34.4  5554.6    34.8
  5566.2    35.5
BR U #Mann= 5
  4393.2      .2    4700      .1  4982.6     .04 5011.42      .1    5300     .99
BR U Banks=4982.6,5011.42
BR D #Sta/Elev= 51
  4393.2    34.8  4574.9    34.4  4644.8   33.39  4665.1    33.1  4694.1    33.5
    4700   33.47  4771.8   33.07 4795.43   32.94  4825.6   32.72 4841.45    32.6
  4883.1   32.79 4889.38   32.82 4935.49   33.18  4937.9    33.1  4982.6   31.59
 4988.89   28.79    4989   28.75 4989.11    28.7 4997.74   24.86 4998.91    23.8
 5000.09   23.76 5000.72    24.4 5002.27   24.84 5007.43   29.82  5011.2   30.87
 5011.42   30.93 5013.69   31.05  5013.8   31.05 5013.91   31.06 5061.52   33.48
  5089.2   33.52 5111.53   33.55  5144.1   33.83 5155.02   33.92    5200   33.59
 5207.47   33.54  5245.8   33.72  5286.3    33.9  5295.2   33.93    5300   33.94
  5305.2   33.96  5353.3    34.1  5365.2   34.05  5404.6    33.9  5422.3    33.3
  5427.5    33.5  5434.2   33.57  5437.4    33.6  5452.5    34.3  5554.6    34.7
  5566.2    35.4
BR D #Mann= 5
  4393.2      .2    4700      .1  4982.6     .04 5011.42      .1    5300     .99
BR D Banks=4982.6,5011.42
BC Design=,, 0 ,, 0 ,,,,,,
BC HTab HWMax=35.49
BC Use User HTab Curves=0
BC User HTab FreeFlow(D)= 0

Type RM Length L Ch R = 1 ,12581.4 ,6.6,6.6,6.6
BEGIN DESCRIPTION:
Downstream Section of Bridge/Culvert/Weir
END DESCRIPTION:
XS GIS Cut Line= 6
      3143990.03     13817563.37      3144173.12     13817342.13
      3144309.81     13817255.14      3144449.65     13817200.05
      3144541.28     13817129.72      3144875.75     13816817.28
#Sta/Elev= 30
  4393.2   34.73  4574.9   34.33  4665.1   33.03  4694.1   33.43    4700    33.4
 4795.43   32.87 4841.45   32.53 4889.38   32.75 4935.49   33.11  4982.6   31.52
 4997.74   24.79 4998.91   23.73 5000.09   23.69 5000.72   24.33 5002.27   24.77
 5007.43   29.75 5011.42   30.86 5061.52   33.41 5111.53   33.48 5155.02   33.85
 5207.47   33.47    5300   33.87  5353.3   34.03  5404.6   33.83  5422.3   33.23
  5427.5   33.43  5437.4   33.53  5452.5   34.23  5554.6   34.63  5566.2   35.33
#Mann= 5 , 1 , 0
  4393.2      .2       0    4700      .1       0  4982.6     .04       0
 5011.42      .1       0    5300     .99       0
#XS Ineff= 2 , 0
       0  4986.7    32.4    5014       0    32.4
Permanent Ineff=
       F       F
Bank Sta=4982.6,5011.42
XS Rating Curve= 0 ,0
Exp/Cntr=0.5,0.3

Type RM Length L Ch R = 1 ,12574.8 ,489.3,154.2,119.8
BEGIN DESCRIPTION:
Cross Section 12574.8-Interpolated
END DESCRIPTION:
XS GIS Cut Line= 4
      3143902.96     13817946.35      3144260.06     13817456.33
      3144621.14     13817084.62      3144874.52     13816851.88
#Sta/Elev= 30
  4054.8      35  4341.3    34.3  4448.6    32.4  4502.3      33  4520.2    32.8
  4541.1    33.7  4664.6    34.5  4699.5   34.43  4821.8    34.2    4901    32.4
  4940.7    33.1  4951.4    32.7  4973.6   32.22  4982.5   30.71  4991.4   29.72
  4997.2   25.26  4998.2   24.17  4998.3   23.89  4999.7   23.64  5001.6   23.97
  5004.1   26.86  5012.4   29.08  5019.6   31.41  5027.9    33.1  5035.4    33.6
  5204.7    33.8  5283.6    33.5    5300   34.62  5315.2    35.2  5523.4    35.5
#Mann= 5 , 1 , 0
  4054.8      .2       0  4699.5      .1       0  4973.6     .04       0
  5019.6      .1       0    5300      .2       0
Bank Sta=4973.6,5019.6
XS Rating Curve= 0 ,0
Exp/Cntr=0.3,0.1

Type RM Length L Ch R = 1 ,12420.6 ,703,696.9,695
BEGIN DESCRIPTION:
Cross Section 12420.6
END DESCRIPTION:
XS GIS Cut Line= 4
      3143920.09      13818834.3      3144566.11     13817329.37
      3144608.56      13817230.9      3144913.03     13816861.07
#Sta/Elev= 30
  3287.6    40.7  3303.9    39.5  3326.1    35.4  3336.5    34.4  3434.5    34.1
  3499.8    32.1    4000   33.53  4250.6    34.3  4283.3    32.3  4315.9    31.7
  4348.6    32.3  4381.2      34  4675.1    33.1    4724    31.8  4838.3      34
  4913.6    32.3  4936.2    32.6  4973.6   31.14  4991.4   28.64  4998.3   22.81
  4999.7   22.56  5001.6   22.89  5004.1   25.78  5019.6   30.33  5032.6    33.8
  5038.7      34    5190    33.8  5248.3      32  5294.4      34  5511.6    35.4
#Mann= 4 , 1 , 0
  3287.6     .99       0    4000      .1       0  4973.6     .04       0
  5019.6      .1       0
#XS Ineff= 2 , 0
       0  4250.6    34.3  5038.7       0      34
Permanent Ineff=
       F       F
Bank Sta=4973.6,5019.6
XS Rating Curve= 0 ,0
Exp/Cntr=0.3,0.1

Type RM Length L Ch R = 1 ,11723.7 ,763.9,699.7,610.5
BEGIN DESCRIPTION:
Cross Section 11723.7-Interpolated
END DESCRIPTION:
XS GIS Cut Line= 4
      3144974.73     13818563.77        3145153.     13817743.75
      3145325.75     13817308.66      3145556.09     13816675.22
#Sta/Elev= 30
  3931.8   35.32  4126.8   34.23  4176.8   31.63  4236.8   31.46  4311.8   34.43
  4466.8   34.02    4500   32.86  4516.8   32.28  4761.8   33.05    4806   31.99
    4921   32.44    4951   31.52    4971   29.82    4986   26.46  4992.2   23.41
  4999.9   22.41  5007.8      23  5008.3   22.37  5021.6   29.71    5036    34.2
    5161   30.99    5196   32.44  5500.1   33.74  5544.1   33.93  5579.1    32.9
  5644.1   34.43  5879.1   34.09  5899.1   33.21  5913.1    33.4  5913.2    35.4
#Mann= 5 , 1 , 0
  3931.8      .2       0    4500      .1       0    4971     .04       0
  5021.6      .1       0  5500.1      .2       0
#XS Ineff= 2 , 0
       0  4311.8   34.43  5644.1       0   34.43
Permanent Ineff=
       F       F
Bank Sta=4971,5021.6
XS Rating Curve= 0 ,0
Exp/Cntr=0.3,0.1