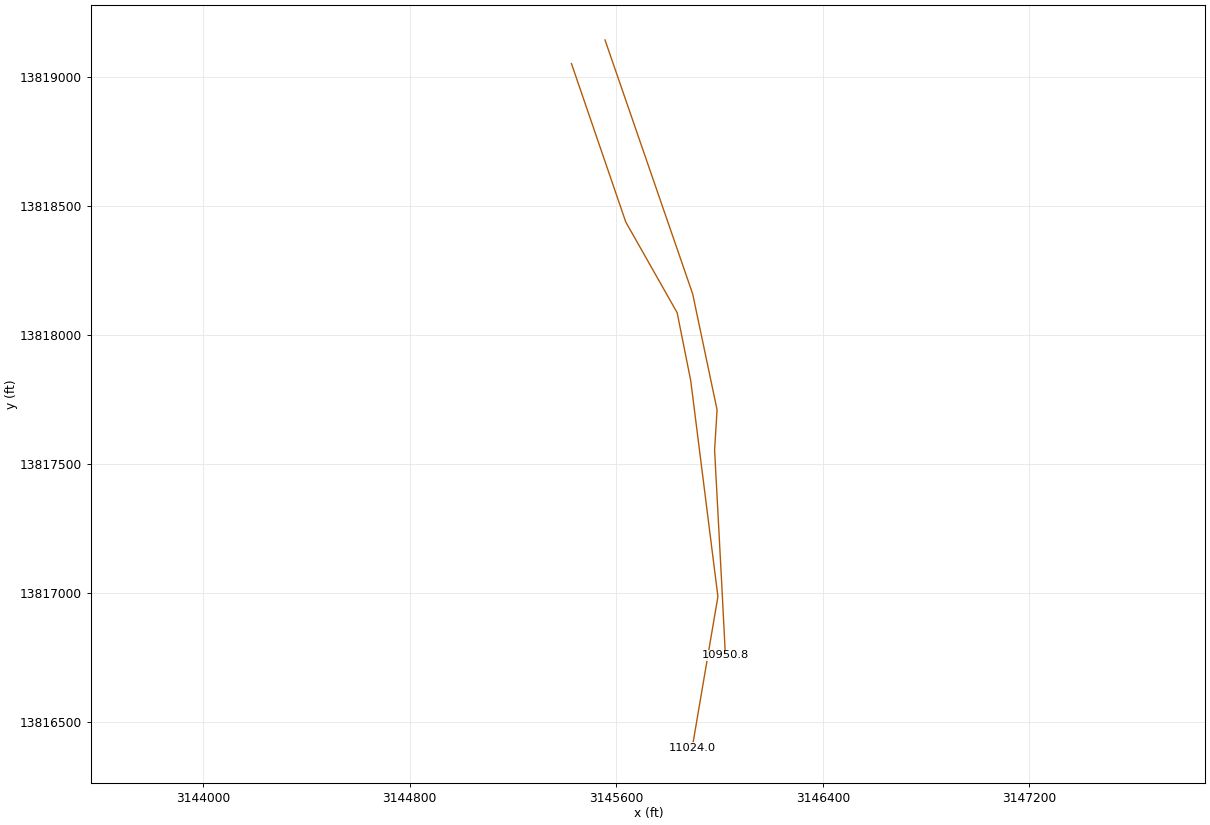
HEC-RAS study C103-00-00.PRJ: C103-00-00

--- C103-00-00.g01 (geometry) --- (continued)

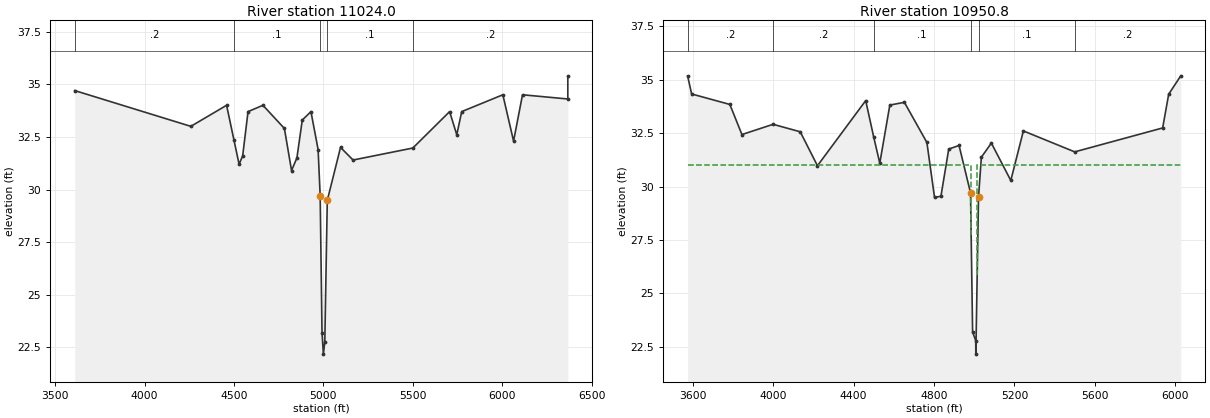
Type RM Length L Ch R = 1 ,11024.0 ,74.6,73.2,73
BEGIN DESCRIPTION:
Cross Section 11024.0-Interpolated
END DESCRIPTION:
XS GIS Cut Line= 6
      3145426.52     13819052.02      3145637.09     13818437.86
      3145835.96     13818086.91      3145888.61     13817823.69
      3145993.89     13816987.26      3145894.46     13816402.34
#Sta/Elev= 30
  3609.2    34.7  4258.5      33  4458.5      34    4500   32.34  4528.5    31.2
  4548.5    31.6  4578.5    33.7  4661.8      34  4781.8    32.9  4821.8    30.9
  4851.8    31.5  4881.8    33.3  4930.3    33.7  4970.3    31.9  4981.9   29.69
  4992.2   23.18  4999.9   22.18  5007.8   22.77  5021.6   29.48  5095.7      32
  5165.7    31.4    5500   31.97  5705.7    33.7  5745.7    32.6  5773.3    33.7
  6003.3    34.5  6063.3    32.3  6113.3    34.5  6366.6    34.3  6366.7    35.4
#Mann= 5 , 1 , 0
  3609.2      .2       0    4500      .1       0  4981.9     .04       0
  5021.6      .1       0    5500      .2       0
#XS Ineff= 2 , 0
       0  4661.8      34  6003.3       0    34.5
Permanent Ineff=
       F       F
Bank Sta=4981.9,5021.6
XS Rating Curve= 0 ,0
Exp/Cntr=0.5,0.3

Type RM Length L Ch R = 1 ,10950.8 ,121.2,121.2,121.2
BEGIN DESCRIPTION:
Upstream Section of Bridge/Culvert/Weir
END DESCRIPTION:
XS GIS Cut Line= 6
      3145556.57     13819143.28      3145896.09     13818159.69
      3145990.64     13817710.55      3145981.02     13817554.72
      3146008.82     13817033.48      3146022.88     13816759.07
#Sta/Elev= 30
    3575   35.18    3595   34.34    3785   33.85    3845   32.44    4000   32.92
    4135   32.57  4220.6   30.98  4460.6   34.03    4500   32.34  4530.6    31.1
  4580.6   33.82  4652.9   33.95  4764.9   32.07  4802.8    29.5  4834.7   29.55
  4873.5   31.76  4924.8   31.93  4981.9   29.71  4992.2    23.2  5007.8   22.79
  5008.3   22.16  5021.6    29.5  5035.8   31.38  5085.5   32.04  5182.2   30.29
  5244.7   32.61    5500   31.63  5937.4   32.75  5967.4   34.33  6027.4   35.19
#Mann= 6 , 1 , 0
    3575      .2       0    4000      .2       0    4500      .1       0
  4981.9     .04       0  5021.6      .1       0    5500      .2       0
#XS Ineff= 2 , 0
       0    4985      31    5015       0      31
Permanent Ineff=
       F       F
Bank Sta=4981.9,5021.6
XS Rating Curve= 0 ,0
Exp/Cntr=0.5,0.3