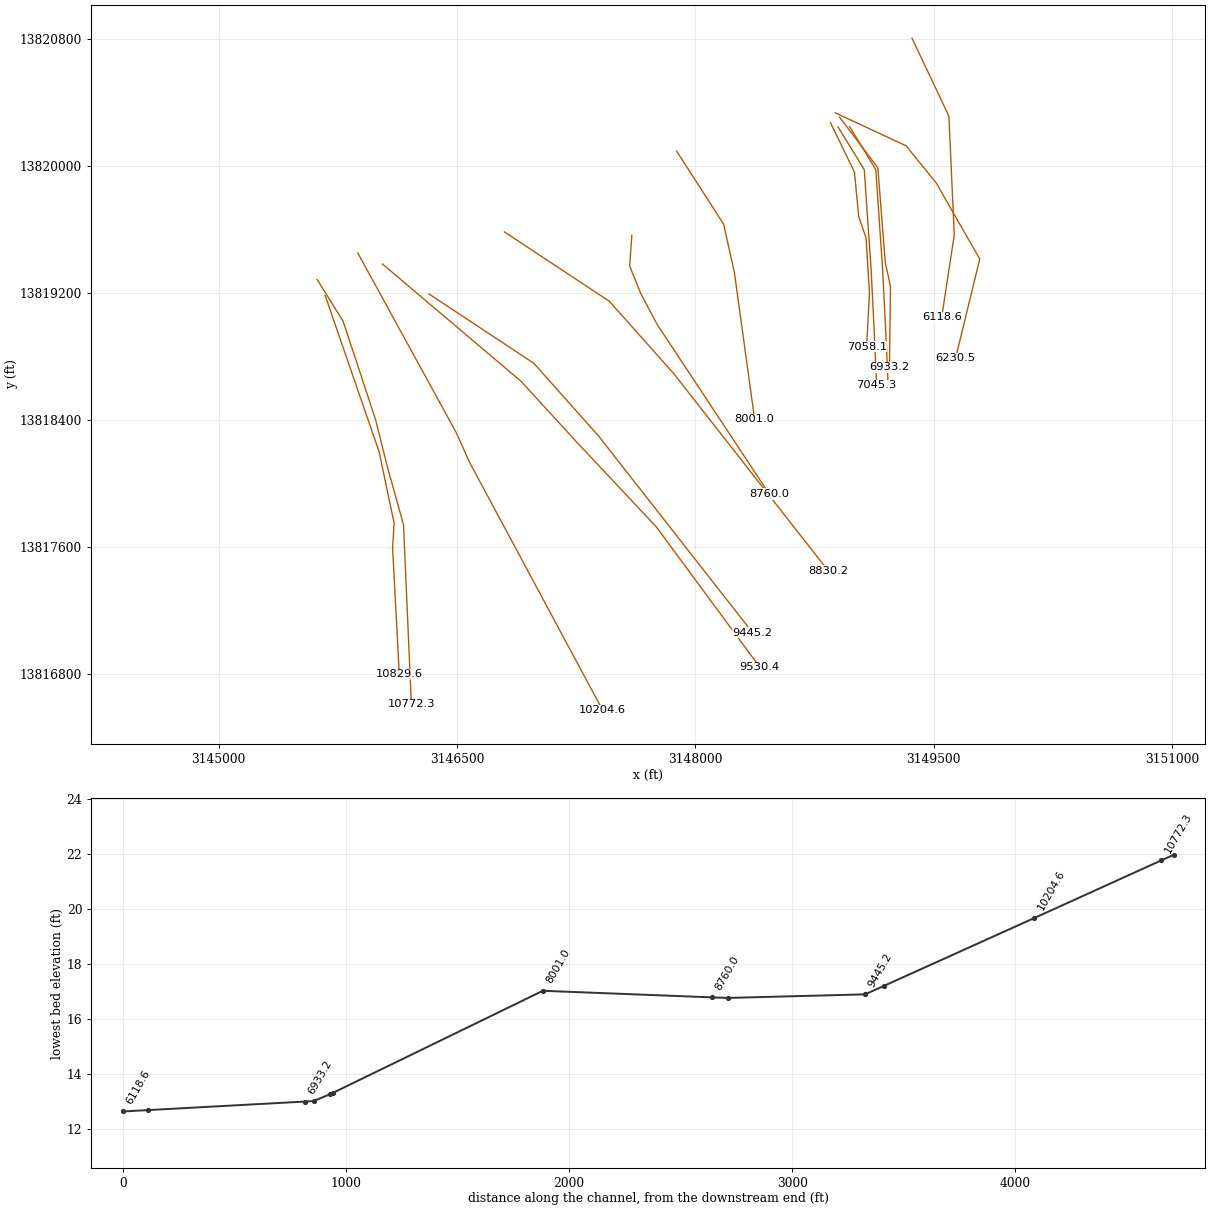
HEC-RAS study C103-00-00.PRJ: C103-00-00

--- C103-00-00.g01 (geometry) --- (continued)

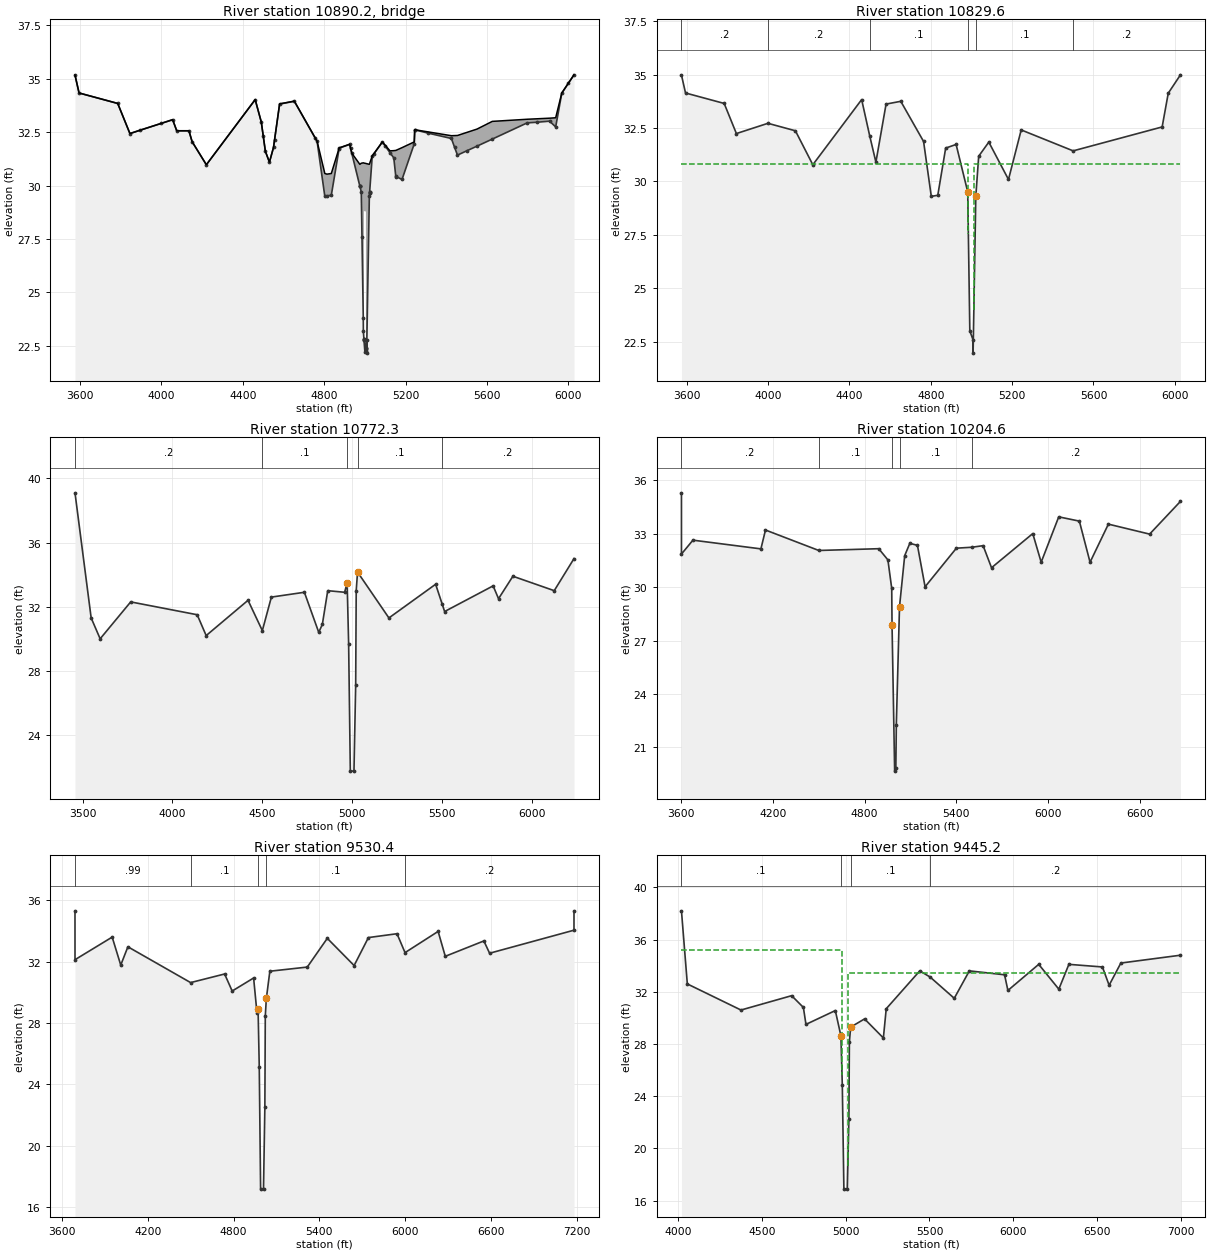
Type RM Length L Ch R = 3 ,10890.2 ,,,
BEGIN DESCRIPTION:
REVEILLE ROAD
Structure ID: C03-7
END DESCRIPTION:
Bridge Culvert--1,0,-1,-1, 0
Deck Dist Width WeirC Skew NumUp NumDn MinLoCord MaxHiCord MaxSubmerge Is_Ogee
10,101.2,2.6,0, 51, 51, , , 0.95, 0, 1,1,,
    3575    3595    3785    3845    4055    4075    4135  4150.6  4220.6  4460.6
  4490.6  4510.6  4530.6  4550.6  4580.6  4652.9  4764.9  4802.8  4813.4  4834.7
  4873.5  4924.8  4935.5 4974.89  4981.9  4991.8  4992.2 4994.91    4995 5004.89
    5005  5007.8  5008.3  5021.6  5035.8  5085.5  5123.1  5141.7  5151.5  5182.2
  5242.3  5244.7  5424.7  5454.7  5550.7  5625.7  5797.4  5907.4  5937.4  5967.4
  6027.4
   35.18   34.34   33.85   32.44   33.09   32.57   32.57   32.06   30.98   34.03
   32.98   31.61    31.1   31.79   33.83   33.96   32.08   30.57   30.54   30.57
   31.77   31.94   31.52      31   31.05   31.07   31.07   31.06   31.06   31.04
   31.04   31.03   31.03      31   31.39   32.05   31.63   31.64   31.65   31.78
   32.05   32.62   32.34   32.35   32.65   33.01   33.11   33.16   33.18   34.34
   35.19
   35.18   34.34   33.85   32.44   33.09   32.57   32.57   32.06   30.98   34.03
   32.98   31.61    31.1   31.79   33.82   33.95   32.07    29.5   29.52   29.55
   31.76   31.93   31.51   29.98   29.71   23.79    23.2   22.82   28.81   28.79
   22.41   22.79   22.16    29.5   31.38   32.04   31.54    31.3   30.44   30.29
   31.96   32.61   32.21   31.43   31.85   32.18   32.94   33.02   32.75   34.33
   35.19
    3575    3595    3785    3845    4055    4075    4135  4150.6  4220.6  4460.6
  4490.6  4510.6  4530.6  4550.6  4580.6  4652.9  4764.9  4802.8  4813.4  4834.7
  4873.5  4924.8  4935.5 4974.89  4981.9  4991.8  4992.2 4994.91    4995 5004.89
    5005  5007.8  5008.3  5021.6  5035.8  5085.5  5123.1  5141.7  5151.5  5182.2
  5242.3  5244.7  5424.7  5454.7  5550.7  5625.7  5797.4  5907.4  5937.4  5967.4
  6027.4
   35.18   34.34   33.85   32.44   33.09   32.57   32.57   32.06   30.98   34.03
   32.98   31.61    31.1   31.79   33.83   33.96   32.08   30.57   30.54   30.57
   31.77   31.94   31.52      31   31.05   31.07   31.07   31.06   31.06   31.04
   31.04   31.03   31.03      31   31.39   32.05   31.63   31.64   31.65   31.78
   32.05   32.62   32.34   32.35   32.65   33.01   33.11   33.16   33.18   34.34
   35.19
   35.02   34.18   33.69   32.28   32.93   32.41   32.41    31.9   30.82   33.87
   32.82   31.45   30.94   31.63   33.66   33.79   31.91   29.34   29.36   29.39
    31.6   31.77   31.35   29.82   29.55   23.63   23.04   22.66   28.65   28.63
   22.25   22.63      22   29.34   31.22   31.88   31.38   31.14   30.28   30.13
    31.8   32.45   32.05   31.27   31.69   32.02   32.78   32.86   32.59   34.17
   35.03
BR Coef= 1 , 1 , 0 ,1.25, 0 ,,,0.8,0,2,0,
WSPro=,,,, 1 ,,,, 0 ,,,, 0 ,,,,-1 ,-1 ,-1 , 0 , 0 , 0 , 0 , 0
BR U #Sta/Elev= 78
    3575   35.18    3595   34.34    3785   33.85    3845   32.44    3895    32.6
    4000   32.92    4055   33.09    4075   32.57    4135   32.57  4150.6   32.06
  4220.6   30.98  4460.6   34.03  4490.6   32.98    4500   32.34  4510.6   31.61
  4530.6    31.1  4550.6   31.79    4556   32.16  4580.6   33.82  4652.9   33.95
  4754.2   32.25  4764.9   32.07  4802.8    29.5  4813.4   29.52  4834.7   29.55
  4872.6   31.71  4873.5   31.76  4924.8   31.93  4929.2   31.76  4935.5   31.51
 4974.89   29.98    4975   29.98 4975.11   29.97  4981.9   29.71  4985.4   27.62
  4991.8   23.79  4992.2    23.2 4994.91   22.82    4995    22.8  4995.1   22.79
  4995.3   22.76  4999.9    22.2    5004   22.27  5004.6   22.35 5004.89   22.39
    5005   22.41  5007.8   22.79  5008.3   22.16  5021.6    29.5 5022.89   29.67
    5023   29.69 5023.11    29.7  5035.8   31.38  5042.3   31.47  5085.5   32.04
  5099.5   31.86  5123.1   31.54  5141.7    31.3  5151.5   30.44  5154.6   30.42
  5182.2   30.29  5242.3   31.96  5244.7   32.61  5246.9   32.61  5310.7   32.46
  5424.7   32.21  5440.7   31.79  5454.7   31.43    5500   31.63  5550.7   31.85
  5625.7   32.18  5797.4   32.94  5845.5   32.97  5907.4   33.02  5937.4   32.75
  5967.4   34.33    6000    34.8  6027.4   35.19
BR U #Mann= 6
    3575      .2    4000      .2    4500      .1  4981.9     .04  5021.6      .1
    5500      .2
BR U Banks=4981.9,5021.6
BR D #Sta/Elev= 78
    3575   35.02    3595   34.18    3785   33.69    3845   32.28    3895   32.44
    4000   32.76    4055   32.93    4075   32.41    4135   32.41  4150.6    31.9
  4220.6   30.82  4460.6   33.87  4490.6   32.82    4500   32.18  4510.6   31.45
  4530.6   30.94  4550.6   31.63    4556      32  4580.6   33.66  4652.9   33.79
  4754.2   32.09  4764.9   31.91  4802.8   29.34  4813.4   29.36  4834.7   29.39
  4872.6   31.55  4873.5    31.6  4924.8   31.77  4929.2    31.6  4935.5   31.35
 4974.89   29.82    4975   29.82 4975.11   29.81  4981.9   29.55  4985.4   27.46
  4991.8   23.63  4992.2   23.04 4994.91   22.66    4995   22.64  4995.1   22.63
  4995.3    22.6  4999.9   22.04    5004   22.11  5004.6   22.19 5004.89   22.23
    5005   22.25  5007.8   22.63  5008.3      22  5021.6   29.34 5022.89   29.51
    5023   29.53 5023.11   29.54  5035.8   31.22  5042.3   31.31  5085.5   31.88
  5099.5    31.7  5123.1   31.38  5141.7   31.14  5151.5   30.28  5154.6   30.26
  5182.2   30.13  5242.3    31.8  5244.7   32.45  5246.9   32.45  5310.7    32.3
  5424.7   32.05  5440.7   31.63  5454.7   31.27    5500   31.47  5550.7   31.69
  5625.7   32.02  5797.4   32.78  5845.5   32.81  5907.4   32.86  5937.4   32.59
  5967.4   34.17    6000   34.64  6027.4   35.03
BR D #Mann= 6
    3575      .2    4000      .2    4500      .1  4981.9     .04  5021.6      .1
    5500      .2
BR D Banks=4981.9,5021.6
BC Design=,, 0 ,, 0 ,,,,,,
BC HTab HWMax=35.19
BC Use User HTab Curves=0
BC User HTab FreeFlow(D)= 0

Type RM Length L Ch R = 1 ,10829.6 ,57.3,57.3,57.3
BEGIN DESCRIPTION:
Downstream Section of Bridge/Culvert/Weir
END DESCRIPTION:
XS GIS Cut Line= 6
      3145670.33     13819185.09      3146009.85     13818201.51
       3146104.4     13817752.37      3146094.78     13817596.54
      3146122.58      13817075.3      3146136.64     13816800.88
#Sta/Elev= 30
    3575   34.98    3595   34.14    3785   33.65    3845   32.24    4000   32.72
    4135   32.37  4220.6   30.78  4460.6   33.83    4500   32.14  4530.6    30.9
  4580.6   33.62  4652.9   33.75  4764.9   31.87  4802.8    29.3  4834.7   29.35
  4873.5   31.56  4924.8   31.73  4981.9   29.51  4992.2      23  5007.8   22.59
  5008.3   21.96  5021.6    29.3  5035.8   31.18  5085.5   31.84  5182.2   30.09
  5244.7   32.41    5500   31.43  5937.4   32.55  5967.4   34.13  6027.4   34.99
#Mann= 6 , 1 , 0
    3575      .2       0    4000      .2       0    4500      .1       0
  4981.9     .04       0  5021.6      .1       0    5500      .2       0
#XS Ineff= 2 , 0
       0    4985    30.8    5012       0    30.8
Permanent Ineff=
       F       F
Bank Sta=4981.9,5021.6
XS Rating Curve= 0 ,0
Exp/Cntr=0.5,0.3

Type RM Length L Ch R = 1 ,10772.3 ,444.1,567.7,697.2
BEGIN DESCRIPTION:
Cross Section 10772.3-Interpolated
END DESCRIPTION:
XS GIS Cut Line= 6
      3145619.54     13819285.99      3145783.32     13819022.78
      3145988.04     13818402.76      3146064.08      13818098.6
      3146163.52      13817741.8      3146213.03     13816612.88
#Sta/Elev= 30
  3457.4    39.1  3547.4    31.3  3597.4      30  3767.4    32.3  4137.4    31.5
  4187.4    30.2  4420.3    32.4    4500   30.51  4550.3    32.6  4733.9    32.9
  4813.9    30.4  4833.9    30.9  4863.9      33    4958    32.9 4971.88   33.49
 4980.18   29.69 4989.58   21.76 5009.88   21.75 5019.38    27.1 5022.38   33.01
 5029.78   34.16  5204.3    31.3  5464.3    33.4    5500   32.19  5514.3    31.7
  5784.3    33.3  5814.3    32.5  5894.3    33.9  6124.3      33  6234.3      35
#Mann= 5 , 1 , 0
  3457.4      .2       0    4500      .1       0 4971.88    .045       0
 5029.78      .1       0    5500      .2       0
Bank Sta=4971.88,5029.78
XS Rating Curve= 0 ,0
Exp/Cntr=0.3,0.1

Type RM Length L Ch R = 1 ,10204.6 ,512.3,674.2,867.5
BEGIN DESCRIPTION:
Cross Section 10204.6-Interpolated
Located At: DS REVEILLE STREET
END DESCRIPTION:
XS GIS Cut Line= 4
      3145876.01      13819452.1      3146496.64     13818319.59
      3146579.82     13818134.04        3147418.     13816572.85
#Sta/Elev= 30
  3600.9    35.3    3601   31.86    3676   32.64    4121   32.15    4151   33.21
    4500   32.06  4892.4   32.16  4952.4   31.53  4977.4   29.93  4979.5   27.89
  4996.6   19.66  5004.4   19.81  5007.6   22.28  5028.4    28.9  5062.4   31.77
  5095.8   32.46  5145.8   32.35  5195.8   30.02  5400.8   32.19    5500   32.24
  5575.8   32.33  5630.8   31.09  5900.8   33.01  5955.8    31.4  6070.8   33.95
  6205.8   33.71  6275.8    31.4  6395.8   33.54  6665.8   32.98  6867.7   34.82
#Mann= 5 , 1 , 0
  3600.9      .2       0    4500      .1       0  4979.5    .045       0
  5028.4      .1       0    5500      .2       0
Bank Sta=4979.5,5028.4
XS Rating Curve= 0 ,0
Exp/Cntr=0.3,0.1

Type RM Length L Ch R = 1 ,9530.4  ,85,85.2,86.9
BEGIN DESCRIPTION:
Cross Section 9530.4-Interpolated
END DESCRIPTION:
XS GIS Cut Line= 5
      3146030.96     13819383.02      3146902.11     13818645.89
      3147258.62     13818256.97      3147755.58     13817727.61
      3148406.13      13816845.5
#Sta/Elev= 30
  3691.1    35.3  3691.2   32.12  3951.2   33.59  4011.2   31.77  4061.2   32.96
    4500   30.63  4737.9   31.19  4790.7   30.08  4940.7   30.93  4964.5   28.63
 4971.88   28.93 4980.18   25.13 4989.58    17.2 5009.88   17.19 5019.38   22.54
 5022.38   28.45 5029.78    29.6  5054.3   31.37  5316.1   31.64  5456.1   33.51
  5643.8   31.74  5743.8   33.56  5943.8   33.81    6000   32.58  6231.5   33.96
  6281.5   32.34  6551.5   33.34  6591.5   32.54  7181.9   34.04    7182    35.3
#Mann= 5 , 1 , 0
  3691.1     .99       0    4500      .1       0 4971.88    .045       0
 5029.78      .1       0    6000      .2       0
Bank Sta=4971.88,5029.78
XS Rating Curve= 0 ,0
Exp/Cntr=0.5,0.3

Type RM Length L Ch R = 1 ,9445.2  ,615,615,615
BEGIN DESCRIPTION:
Upstream Section of Bridge/Culvert/Weir
END DESCRIPTION:
XS GIS Cut Line= 5
     3146323.583    13819194.519      3146394.58      13819147.6
      3146983.51      13818758.4      3147390.86     13818301.17
     3148360.959    13817062.911
#Sta/Elev= 30
  4020.8    38.2  4055.8    32.6  4375.8    30.6    4678    31.7    4748    30.8
  4763.4    29.5  4938.5   30.56  4971.9   28.62  4980.2   24.82  4989.6   16.89
  5009.9   16.88  5019.4   22.23  5022.4   28.14  5029.8   29.29  5112.9   29.92
  5225.1   28.46  5242.2    30.7  5442.2    33.6  5503.7   33.13  5647.9    31.5
  5737.9    33.6  5947.9    33.3  5967.9    32.1  6151.6    34.1  6271.6    32.2
  6331.6    34.1  6531.6    33.9  6571.6    32.5  6641.6    34.2  6997.1    34.8
#Mann= 4 , 1 , 0
  4020.8      .1       0  4971.9    .045       0  5029.8      .1       0
  5503.7      .2       0
#XS Ineff= 2 , 0
       0  4978.5    35.2  5013.1       0    33.4
Permanent Ineff=
       F       F
Bank Sta=4971.9,5029.8
XS Rating Curve= 0 ,0
Exp/Cntr=0.5,0.3

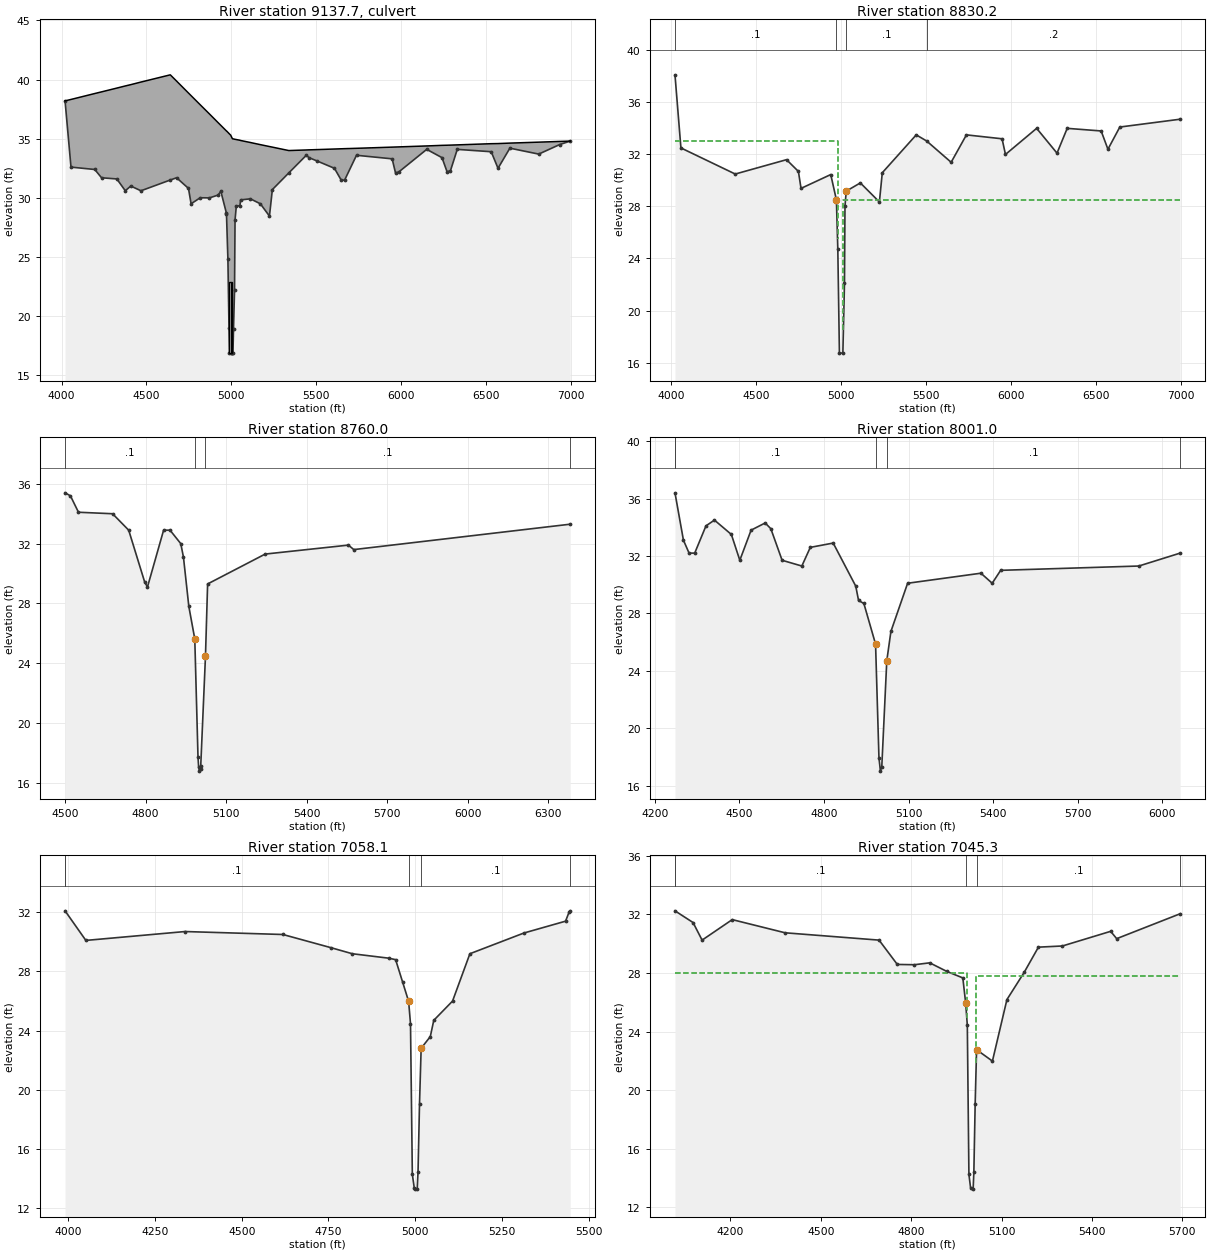
Type RM Length L Ch R = 2 ,9137.7  ,,,
BEGIN DESCRIPTION:
INTERSTATE 45
Structure ID: C03-6
END DESCRIPTION:
Bridge Culvert--1,0,-1,-1, 0
Deck Dist Width WeirC Skew NumUp NumDn MinLoCord MaxHiCord MaxSubmerge Is_Ogee
10,595,3,0, 57, 57, , , 0.95, 0, 1,1,,
  4020.8  4055.8  4195.8  4235.8  4325.8  4375.8    4408    4468  4640.8    4678
    4748  4763.4  4817.1  4871.8  4923.1  4938.5  4971.3  4971.9  4980.2  4986.8
  4989.6  4996.7  5004.5  5006.7  5009.9  5013.3  5019.4  5022.4  5029.8  5051.2
  5055.2  5112.9  5171.4  5225.1  5242.2  5339.1  5442.2  5457.9  5503.7  5607.9
  5647.9  5667.9  5737.9  5947.9  5967.9  5987.9  6151.6  6241.6  6271.6  6291.6
  6331.6  6531.6  6571.6  6641.6  6811.6    6934  6997.1
    38.2   38.32   38.82   38.96   39.28   39.46   39.57   39.79    40.4   39.87
   38.86   38.64   37.87   37.09   36.35   36.13   35.66   35.66   35.54   35.44
    35.4    35.3   35.07      35   34.99   34.98   34.96   34.95   34.93   34.87
   34.85   34.68    34.5   34.34   34.29      34   34.05   34.06   34.08   34.13
   34.15   34.16   34.19   34.29    34.3   34.31   34.39   34.44   34.45   34.46
   34.48   34.58   34.59   34.63   34.71   34.77    34.8
    38.2    32.6    32.4    31.7    31.6    30.6      31    30.6   31.51    31.7
    30.8    29.5   30.01      30   30.24   30.56   28.72   28.62   24.82   18.98
   16.89   16.89    16.9   16.89   16.88   18.91   22.23   28.14   29.29   29.35
   29.83   29.92    29.5   28.46    30.7   32.11    33.6    33.4   33.13    32.5
    31.5    31.5    33.6    33.3    32.1    32.2    34.1    33.4    32.2    32.3
    34.1    33.9    32.5    34.2    33.7    34.5    34.8
  4020.8  4055.8  4195.8  4235.8  4325.8  4375.8    4408    4468  4640.8    4678
    4748  4763.4  4817.1  4871.8  4923.1  4938.5  4971.3  4971.9  4980.2  4986.8
  4989.6  4996.7  5004.5  5006.7  5009.9  5013.3  5019.4  5022.4  5029.8  5051.2
  5055.2  5112.9  5171.4  5225.1  5242.2  5339.1  5442.2  5457.9  5503.7  5607.9
  5647.9  5667.9  5737.9  5947.9  5967.9  5987.9  6151.6  6241.6  6271.6  6291.6
  6331.6  6531.6  6571.6  6641.6  6811.6    6934  6997.1
    38.2   38.32   38.82   38.96   39.28   39.46   39.57   39.79    40.4   39.87
   38.86   38.64   37.87   37.09   36.35   36.13   35.66   35.66   35.54   35.44
    35.4    35.3   35.07      35   34.99   34.98   34.96   34.95   34.93   34.87
   34.85   34.68    34.5   34.34   34.29      34   34.05   34.06   34.08   34.13
   34.15   34.16   34.19   34.29    34.3   34.31   34.39   34.44   34.45   34.46
   34.48   34.58   34.59   34.63   34.71   34.77    34.8
   38.07   32.47   32.27   31.57   31.47   30.47   30.87   30.47   31.38   31.57
   30.67   29.37   29.88   29.87   30.11   30.43   28.59   28.49   24.69   18.85
   16.76   16.76   16.77   16.76   16.75   18.78    22.1   28.01   29.16   29.22
    29.7   29.79   29.37   28.33   30.57   31.98   33.47   33.27      33   32.37
   31.37   31.37   33.47   33.17   31.97   32.07   33.97   33.27   32.07   32.17
   33.97   33.77   32.37   34.07   33.57   34.37   34.67
BR Coef= 1 , 0 , 0 ,1.25, 0 ,,,0.8,-1,2,0,
WSPro=,,,, 1 ,,,, 0 ,,,, 0 ,,,,-1 ,-1 ,-1 , 0 , 0 , 0 , 0 , 0
Culvert=2,6,7,595,0.015,0.4,1,8,1,16.9,4992.2,16.2,4992.2,Culvert #1  , 0 ,10
Culvert Bottom n=0.015
Culvert=2,6,7,595,0.015,0.4,1,8,1,16.9,4999.5,16.2,4999.5,Culvert #2  , 0 ,10
Culvert Bottom n=0.015
BR U #Sta/Elev= 57
  4020.8    38.2  4055.8    32.6  4195.8    32.4  4235.8    31.7  4325.8    31.6
  4375.8    30.6    4408      31    4468    30.6  4640.8   31.51    4678    31.7
    4748    30.8  4763.4    29.5  4817.1   30.01  4871.8      30  4923.1   30.24
  4938.5   30.56  4971.3   28.72  4971.9   28.62  4980.2   24.82  4986.8   18.98
  4989.6   16.89  4996.7   16.89  5004.5    16.9  5006.7   16.89  5009.9   16.88
  5013.3   18.91  5019.4   22.23  5022.4   28.14  5029.8   29.29  5051.2   29.35
  5055.2   29.83  5112.9   29.92  5171.4    29.5  5225.1   28.46  5242.2    30.7
  5339.1   32.11  5442.2    33.6  5457.9    33.4  5503.7   33.13  5607.9    32.5
  5647.9    31.5  5667.9    31.5  5737.9    33.6  5947.9    33.3  5967.9    32.1
  5987.9    32.2  6151.6    34.1  6241.6    33.4  6271.6    32.2  6291.6    32.3
  6331.6    34.1  6531.6    33.9  6571.6    32.5  6641.6    34.2  6811.6    33.7
    6934    34.5  6997.1    34.8
BR U #Mann= 4
  4020.8      .1  4971.9    .045  5029.8      .1  5503.7      .2
BR U Banks=4971.9,5029.8
BR D #Sta/Elev= 57
  4020.8   38.07  4055.8   32.47  4195.8   32.27  4235.8   31.57  4325.8   31.47
  4375.8   30.47    4408   30.87    4468   30.47  4640.8   31.38    4678   31.57
    4748   30.67  4763.4   29.37  4817.1   29.88  4871.8   29.87  4923.1   30.11
  4938.5   30.43  4971.3   28.59  4971.9   28.49  4980.2   24.69  4986.8   18.85
  4989.6   16.76  4996.7   16.76  5004.5   16.77  5006.7   16.76  5009.9   16.75
  5013.3   18.78  5019.4    22.1  5022.4   28.01  5029.8   29.16  5051.2   29.22
  5055.2    29.7  5112.9   29.79  5171.4   29.37  5225.1   28.33  5242.2   30.57
  5339.1   31.98  5442.2   33.47  5457.9   33.27  5503.7      33  5607.9   32.37
  5647.9   31.37  5667.9   31.37  5737.9   33.47  5947.9   33.17  5967.9   31.97
  5987.9   32.07  6151.6   33.97  6241.6   33.27  6271.6   32.07  6291.6   32.17
  6331.6   33.97  6531.6   33.77  6571.6   32.37  6641.6   34.07  6811.6   33.57
    6934   34.37  6997.1   34.67
BR D #Mann= 4
  4020.8      .1  4971.9    .045  5029.8      .1  5503.7      .2
BR D Banks=4971.9,5029.8
BC Design=,, 0 ,, 0 ,,,,,,
BC HTab HWMax=38.2
BC Use User HTab Curves=0
BC User HTab FreeFlow(D)= 0

Type RM Length L Ch R = 1 ,8830.2  ,70.2,70.2,70.2
BEGIN DESCRIPTION:
Downstream Section of Bridge/Culvert/Weir
END DESCRIPTION:
XS GIS Cut Line= 5
     3146798.517    13819585.285      3146869.43     13819538.42
      3147458.35     13819149.22       3147865.7     13818691.99
     3148835.799    13817453.731
#Sta/Elev= 30
  4020.8   38.07  4055.8   32.47  4375.8   30.47    4678   31.57    4748   30.67
  4763.4   29.37  4938.5   30.43  4971.9   28.49  4980.2   24.69  4989.6   16.76
  5009.9   16.75  5019.4    22.1  5022.4   28.01  5029.8   29.16  5112.9   29.79
  5225.1   28.33  5242.2   30.57  5442.2   33.47  5503.7      33  5647.9   31.37
  5737.9   33.47  5947.9   33.17  5967.9   31.97  6151.6   33.97  6271.6   32.07
  6331.6   33.97  6531.6   33.77  6571.6   32.37  6641.6   34.07  6997.1   34.67
#Mann= 4 , 1 , 0
  4020.8      .1       0  4971.9    .045       0  5029.8      .1       0
  5503.7      .2       0
#XS Ineff= 2 , 0
       0  4978.5      33  5013.1       0    28.5
Permanent Ineff=
       F       F
Bank Sta=4971.9,5029.8
XS Rating Curve= 0 ,0
Exp/Cntr=0.5,0.3

Type RM Length L Ch R = 1 ,8760.0  ,761.1,759,729.8
BEGIN DESCRIPTION:
Cross Section 8760.0-Interpolated
END DESCRIPTION:
XS GIS Cut Line= 5
      3147601.08     13819564.32      3147587.21     13819370.22
      3147658.32     13819194.67      3147760.01     13819003.23
      3148466.15     13817935.13
#Sta/Elev= 24
  4499.9    35.4  4519.9    35.2  4549.9    34.1  4676.9      34  4736.9    32.9
  4796.9    29.4  4806.9    29.1  4866.9    32.9  4890.8    32.9  4930.8      32
  4940.8    31.1  4960.8    27.8    4983   25.62    4995   17.71  4997.3   17.05
  5000.2   16.77  5004.4   16.88  5005.1   17.09  5022.8   24.46  5030.8    29.3
  5245.1    31.3  5555.1    31.9  5575.1    31.6  6381.1    33.3
#Mann= 4 , 1 , 0
  4499.9      .1       0    4983    .055       0  5022.8      .1       0
  6381.1      .2       0
Bank Sta=4983,5022.8
XS Rating Curve= 0 ,0
Exp/Cntr=0.3,0.1

Type RM Length L Ch R = 1 ,8001.0  ,931.3,942.9,942.7
BEGIN DESCRIPTION:
Cross Section 8001.0
END DESCRIPTION:
XS GIS Cut Line= 4
      3147882.87     13820093.51      3148178.81     13819633.66
      3148246.91     13819327.21        3148374.      13818404.8
#Sta/Elev= 30
  4271.5    36.4  4301.5    33.1  4321.5    32.2  4341.5    32.2  4381.5    34.1
  4411.5    34.5  4471.5    33.5  4501.5    31.7  4541.5    33.8  4591.5    34.3
  4611.5    33.9  4651.5    31.7  4721.5    31.3  4751.5    32.6  4832.7    32.9
  4912.7    29.9  4922.7    28.9  4941.5   28.69    4983   25.86    4995   17.95
  5000.2   17.01  5005.1   17.33  5022.8    24.7  5037.4   26.74  5096.7    30.1
  5356.7    30.8  5396.7    30.1  5426.7      31  5916.7    31.3  6063.4    32.2
#Mann= 5 , 1 , 0
  4271.5      .2       0  4271.5      .1       0    4983    .045       0
  5022.8      .1       0  6063.4      .2       0
Bank Sta=4983,5022.8
XS Rating Curve= 0 ,0
Exp/Cntr=0.3,0.1

Type RM Length L Ch R = 1 ,7058.1  ,15,12.8,12.5
BEGIN DESCRIPTION:
Cross Section 7058.1-Interpolated
END DESCRIPTION:
XS GIS Cut Line= 6
      3148851.24     13820272.63      3149002.28     13819961.47
      3149029.28     13819680.72      3149075.17     13819548.44
      3149096.77      13819200.2      3149078.95     13818862.27
#Sta/Elev= 26
  3990.8    32.1  4050.8    30.1  4336.7    30.7  4618.7    30.5  4758.7    29.6
  4818.7    29.2  4923.6    28.9  4943.6    28.8  4963.6    27.3  4981.1   25.98
  4986.5   24.47  4991.8   14.29  4997.3   13.38  5000.7    13.3  5005.8   13.29
  5008.2   14.45  5012.5   19.07  5017.2   22.81  5043.6    23.6  5053.6    24.7
  5107.7      26  5157.7    29.2  5313.4    30.6  5433.4    31.4  5443.4      32
  5446.9    32.1
#Mann= 5 , 1 , 0
  3990.8      .2       0  3990.8      .1       0  4981.1     .04       0
  5017.2      .1       0  5446.9      .2       0
Bank Sta=4981.1,5017.2
XS Rating Curve= 0 ,0
Exp/Cntr=0.5,0.3

Type RM Length L Ch R = 1 ,7045.3  ,72.4,72.4,72.4
BEGIN DESCRIPTION:
Upstream Section of Bridge/Culvert/Weir
END DESCRIPTION:
XS GIS Cut Line= 6
      3148899.16     13820246.11      3149064.22     13819975.68
      3149106.95      13819352.5      3149111.15     13819269.04
      3149128.07     13818932.53      3149141.88      13818618.6
#Sta/Elev= 27
  4016.5   32.24  4076.5   31.44  4106.5   30.24  4206.5   31.64    4382   30.74
  4693.7   30.24  4754.2   28.58  4811.1   28.56  4861.8   28.69  4918.8    28.1
  4971.6   27.66  4981.1   25.93  4986.5   24.42  4991.8   14.24  4997.3   13.33
  5005.8   13.24  5008.2    14.4  5012.5   19.02  5017.2   22.76  5069.8   21.98
  5117.9   26.18  5175.2   28.04  5222.4   29.76    5302   29.84  5462.1   30.84
  5482.1   30.34  5692.7   32.04
#Mann= 5 , 1 , 0
  4016.5      .2       0  4016.5      .1       0  4981.1     .04       0
  5017.2      .1       0  5692.7      .2       0
#XS Ineff= 2 , 0
       0  4985.1      28  5016.1       0    27.8
Permanent Ineff=
       F       F
Bank Sta=4981.1,5017.2
XS Rating Curve= 0 ,0
Exp/Cntr=0.5,0.3

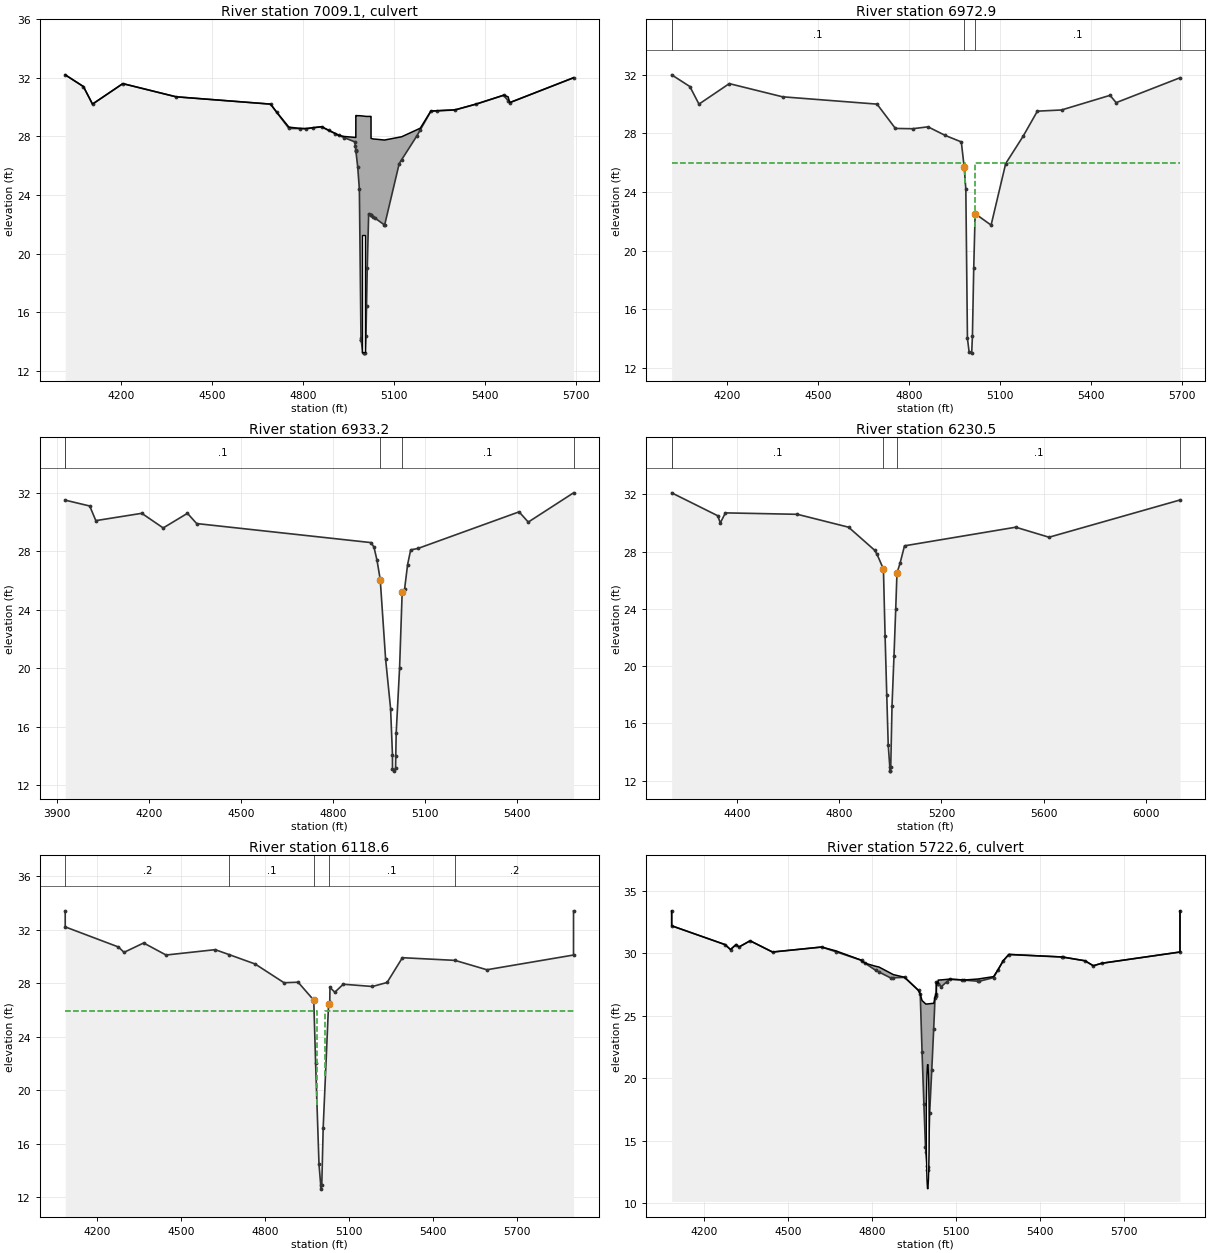
Type RM Length L Ch R = 2 ,7009.1  ,,,
BEGIN DESCRIPTION:
DOVER
Structure ID: C03-5
END DESCRIPTION:
Bridge Culvert--1,0,-1,-1, 0
Deck Dist Width WeirC Skew NumUp NumDn MinLoCord MaxHiCord MaxSubmerge Is_Ogee
10,52.4,3,0, 53, 53, , , 0.95, 0, 1,1,,
  4016.5  4076.5  4106.5  4206.5    4382  4693.7  4714.3  4754.2  4791.8  4811.1
  4832.8  4861.8  4885.8  4907.6  4918.8  4936.9  4971.6  4973.2 4974.79  4974.9
 4975.01  4981.1  4986.5  4991.8  4992.2  4992.4  4997.3  5000.7  5000.9  5005.8
  5008.2  5010.1  5012.5  5017.2 5024.79  5024.9 5025.01  5032.3  5038.6  5068.5
  5069.8  5117.9  5125.8  5175.2  5187.4  5222.4  5241.2    5302  5372.1  5462.1
  5477.1  5482.1  5692.7
    32.2    31.4    30.2    31.6    30.7    30.2   29.64   28.63   28.54   28.53
   28.59   28.66   28.41   28.19   28.07   27.99   27.93   27.93   27.92   29.42
   29.42   29.41   29.41    29.4    29.4    29.4   29.39   29.38   29.38   29.37
   29.36   29.36   29.36   29.36   29.36   29.36   27.86   27.82   27.81   27.75
   27.75   27.94   27.97   28.44   28.56   29.73   29.75   29.81   30.21   30.81
    30.7    30.3      32
    32.2    31.4    30.2    31.6    30.7    30.2   29.63   28.54   28.53   28.52
   28.58   28.65    28.4   28.18   28.06   27.91   27.62   27.33   27.04   27.02
      27   25.89   24.38    14.2   14.13    14.1   13.29   13.21   13.21    13.2
   14.36    16.4   18.98   22.72   22.61   22.61   22.61    22.5   22.41   21.96
   21.94   26.14    26.4      28   28.44   29.72   29.74    29.8    30.2    30.8
   30.43    30.3      32
  4016.5  4076.5  4106.5  4206.5    4382  4693.7  4714.3  4754.2  4791.8  4811.1
  4832.8  4861.8  4885.8  4907.6  4918.8  4936.9  4971.6  4973.2 4974.79  4974.9
 4975.01  4981.1  4986.5  4991.8  4992.2  4992.4  4997.3  5000.7  5000.9  5005.8
  5008.2  5010.1  5012.5  5017.2 5024.79  5024.9 5025.01  5032.3  5038.6  5068.5
  5069.8  5117.9  5125.8  5175.2  5187.4  5222.4  5241.2    5302  5372.1  5462.1
  5477.1  5482.1  5692.7
    32.2    31.4    30.2    31.6    30.7    30.2   29.64   28.63   28.54   28.53
   28.59   28.66   28.41   28.19   28.07   27.99   27.93   27.93   27.92   29.42
   29.42   29.41   29.41    29.4    29.4    29.4   29.39   29.38   29.38   29.37
   29.36   29.36   29.36   29.36   29.36   29.36   27.86   27.82   27.81   27.75
   27.75   27.94   27.97   28.44   28.56   29.73   29.75   29.81   30.21   30.81
    30.7    30.3      32
      32    31.2      30    31.4    30.5      30   29.43   28.34   28.33   28.32
   28.38   28.45    28.2   27.98   27.86   27.71   27.42   27.13   26.84   26.82
    26.8   25.69   24.18      14   13.93    13.9   13.09   13.01   13.01      13
   14.16    16.2   18.78   22.52   22.41   22.41   22.41    22.3   22.21   21.76
   21.74   25.94    26.2    27.8   28.24   29.52   29.54    29.6      30    30.6
   30.23    30.1    31.8
BR Coef= 1 , 0 , 0 ,1.25, 0 ,,,0.8,-1,2,0,
WSPro=,,,, 1 ,,,, 0 ,,,, 0 ,,,,-1 ,-1 ,-1 , 0 , 0 , 0 , 0 , 0
Culvert=2,8,11,52.4,0.015,0.4,1,8,1,13.27,5000.6,13.09,5000.6,Culvert #1  , 0 ,10
Culvert Bottom n=0.015
BR U #Sta/Elev= 53
  4016.5    32.2  4076.5    31.4  4106.5    30.2  4206.5    31.6    4382    30.7
  4693.7    30.2  4714.3   29.63  4754.2   28.54  4791.8   28.53  4811.1   28.52
  4832.8   28.58  4861.8   28.65  4885.8    28.4  4907.6   28.18  4918.8   28.06
  4936.9   27.91  4971.6   27.62  4973.2   27.33 4974.79   27.04  4974.9   27.02
 4975.01      27  4981.1   25.89  4986.5   24.38  4991.8    14.2  4992.2   14.13
  4992.4    14.1  4997.3   13.29  5000.7   13.21  5000.9   13.21  5005.8    13.2
  5008.2   14.36  5010.1    16.4  5012.5   18.98  5017.2   22.72 5024.79   22.61
  5024.9   22.61 5025.01   22.61  5032.3    22.5  5038.6   22.41  5068.5   21.96
  5069.8   21.94  5117.9   26.14  5125.8    26.4  5175.2      28  5187.4   28.44
  5222.4   29.72  5241.2   29.74    5302    29.8  5372.1    30.2  5462.1    30.8
  5477.1   30.43  5482.1    30.3  5692.7      32
BR U #Mann= 5
  4016.5      .2  4016.5      .1  4981.1     .04  5017.2      .1  5692.7      .2
BR U Banks=4981.1,5017.2
BR D #Sta/Elev= 53
  4016.5      32  4076.5    31.2  4106.5      30  4206.5    31.4    4382    30.5
  4693.7      30  4714.3   29.43  4754.2   28.34  4791.8   28.33  4811.1   28.32
  4832.8   28.38  4861.8   28.45  4885.8    28.2  4907.6   27.98  4918.8   27.86
  4936.9   27.71  4971.6   27.42  4973.2   27.13 4974.79   26.84  4974.9   26.82
 4975.01    26.8  4981.1   25.69  4986.5   24.18  4991.8      14  4992.2   13.93
  4992.4    13.9  4997.3   13.09  5000.7   13.01  5000.9   13.01  5005.8      13
  5008.2   14.16  5010.1    16.2  5012.5   18.78  5017.2   22.52 5024.79   22.41
  5024.9   22.41 5025.01   22.41  5032.3    22.3  5038.6   22.21  5068.5   21.76
  5069.8   21.74  5117.9   25.94  5125.8    26.2  5175.2    27.8  5187.4   28.24
  5222.4   29.52  5241.2   29.54    5302    29.6  5372.1      30  5462.1    30.6
  5477.1   30.23  5482.1    30.1  5692.7    31.8
BR D #Mann= 5
  4016.5      .2  4016.5      .1  4981.1     .04  5017.2      .1  5692.7      .2
BR D Banks=4981.1,5017.2
BC Design=,, 0 ,, 0 ,,,,,,
BC HTab HWMax=32.24
BC Use User HTab Curves=0
BC User HTab FreeFlow(D)= 0

Type RM Length L Ch R = 1 ,6972.9  ,39.7,39.7,39.7
BEGIN DESCRIPTION:
Downstream Section of Bridge/Culvert/Weir
END DESCRIPTION:
XS GIS Cut Line= 6
      3148971.53     13820248.26      3149136.58     13819977.82
      3149179.31     13819354.64      3149183.51     13819271.18
      3149200.43     13818934.67      3149214.25     13818620.75
#Sta/Elev= 27
  4016.5      32  4076.5    31.2  4106.5      30  4206.5    31.4    4382    30.5
  4693.7      30  4754.2   28.34  4811.1   28.32  4861.8   28.45  4918.8   27.86
  4971.6   27.42  4981.1   25.69  4986.5   24.18  4991.8      14  4997.3   13.09
  5005.8      13  5008.2   14.16  5012.5   18.78  5017.2   22.52  5069.8   21.74
  5117.9   25.94  5175.2    27.8  5222.4   29.52    5302    29.6  5462.1    30.6
  5482.1    30.1  5692.7    31.8
#Mann= 5 , 1 , 0
  4016.5      .2       0  4016.5      .1       0  4981.1     .04       0
  5017.2      .1       0  5692.7      .2       0
#XS Ineff= 2 , 0
       0  4985.1      26  5016.1       0      26
Permanent Ineff=
       F       F
Bank Sta=4981.1,5017.2
XS Rating Curve= 0 ,0
Exp/Cntr=0.5,0.3

Type RM Length L Ch R = 1 ,6933.2  ,700,702.7,720
BEGIN DESCRIPTION:
Cross Section 6933.2-Interpolated
END DESCRIPTION:
XS GIS Cut Line= 5
      3148908.67     13820307.17      3149149.47     13819988.79
      3149196.48     13819391.74      3149229.39      13819241.3
      3149222.34     13818733.57
#Sta/Elev= 28
    3926    31.5    4006    31.1    4026    30.1    4176    30.6    4246    29.6
  4325.2    30.6  4355.2    29.9  4924.1    28.6  4934.1    28.3  4944.1    27.4
  4954.7   26.07  4972.3   20.62  4988.5   17.26  4994.6   14.11  4994.7   13.12
    5000   12.98  5004.8   13.21  5005.4   13.98  5006.8   15.58  5017.9   20.04
  5026.4   25.25  5034.1    25.4  5044.1    27.1  5054.1    28.1  5078.1    28.2
  5408.1    30.7  5438.1      30  5585.9      32
#Mann= 5 , 1 , 0
    3926      .2       0    3926      .1       0  4954.7     .04       0
  5026.4      .1       0  5585.9      .2       0
Bank Sta=4954.7,5026.4
XS Rating Curve= 0 ,0
Exp/Cntr=0.3,0.1

Type RM Length L Ch R = 1 ,6230.5  ,113.1,111.9,111.2
BEGIN DESCRIPTION:
Cross Section 6230.5-Interpolated
END DESCRIPTION:
XS GIS Cut Line= 6
      3148881.68     13820334.56      3149327.07     13820127.15
      3149517.05     13819893.35      3149574.93     13819791.38
      3149791.05     13819414.31      3149639.25     13818790.77
#Sta/Elev= 25
  4145.9    32.1  4325.9    30.5  4335.9      30  4355.9    30.7  4637.2    30.6
  4837.2    29.7  4938.5    28.1  4948.5    27.8  4973.3   26.78  4979.8   22.11
  4986.3   17.99    4992   14.52  4998.1   12.98  4998.2   12.67  5000.1   12.71
  5001.9   12.96  5006.9   17.25  5014.6   20.73  5021.4   24.01  5026.2    26.5
  5038.5    27.2  5055.7    28.4  5490.3    29.7  5620.3      29  6132.1    31.6
#Mann= 5 , 1 , 0
  4145.9      .2       0  4145.9      .1       0  4973.3    .045       0
  5026.2      .1       0  6132.1      .2       0
Bank Sta=4973.3,5026.2
XS Rating Curve= 0 ,0
Exp/Cntr=0.5,0.3

Type RM Length L Ch R = 1 ,6118.6  ,792,792,792
BEGIN DESCRIPTION:
Upstream Section of Bridge/Culvert/Weir
END DESCRIPTION:
XS GIS Cut Line= 4
      3149364.63     13820804.34       3149596.8     13820313.62
      3149630.61     13819565.52       3149551.5     13819048.07
#Sta/Elev= 30
  4085.7    33.4  4085.8    32.2  4275.8    30.7  4295.8    30.3  4365.8      31
  4445.8    30.1  4621.2    30.5  4671.2   30.13  4763.9   29.43  4867.2   28.03
  4917.4   28.07  4973.3   26.73  4979.8   22.06    4992   14.47  4998.1   12.93
  4998.2   12.62  5001.9   12.91  5006.9    17.2  5026.2   26.45  5030.4   26.57
  5031.1   27.68  5048.5   27.32  5078.5   27.92  5182.9   27.75  5235.1   28.05
  5289.8    29.9  5477.8    29.7  5591.4      29  5900.8    30.1  5900.9    33.4
#Mann= 5 , 1 , 0
  4085.7      .2       0  4671.2      .1       0  4973.3    .045       0
  5026.2      .1       0  5477.8      .2       0
#XS Ineff= 2 , 0
       0    4985    25.9    5015       0    25.9
Permanent Ineff=
       F       F
Bank Sta=4973.3,5026.2
XS Rating Curve= 0 ,0
Exp/Cntr=0.5,0.3

Type RM Length L Ch R = 2 ,5722.6  ,,,
BEGIN DESCRIPTION:
BROADWAY BOULEVARD
Structure ID: C03-4
END DESCRIPTION:
Bridge Culvert--1,0,-1,-1, 0
Deck Dist Width WeirC Skew NumUp NumDn MinLoCord MaxHiCord MaxSubmerge Is_Ogee
10,772,3,0, 56, 56, , , 0.95, 0, 1,1,,
  4085.7  4085.8  4275.8  4295.8  4315.8  4325.8  4365.8  4445.8  4621.2  4671.2
  4763.9  4764.8  4777.1  4813.7  4825.9  4867.2  4877.4  4917.4  4967.1  4973.3
  4979.8  4986.3    4992  4993.5  4998.1  4998.2  5000.1  5001.9  5006.9  5014.6
  5021.4  5026.2  5029.6  5030.4  5031.1  5034.6  5036.8  5037.3  5048.5  5068.8
  5078.5  5124.2  5130.8  5180.1  5182.9  5235.1  5250.7  5269.8  5289.8  5477.8
  5481.4  5561.4  5591.4  5621.4  5900.8  5900.9
    33.4    32.2    30.7    30.3    30.7    30.5      31    30.1    30.5    30.2
   29.44   29.38    29.2   28.96    28.9   28.41   28.29   28.08   27.03   26.74
   26.21   26.08   25.96   25.93   25.94   25.94   25.94   25.95   25.96   25.98
   25.99   26.46   26.71   26.58   27.69   27.62   27.57   27.85   27.87   27.91
   27.93   27.87   27.86   27.94   27.95   28.13   28.67   29.41   29.91   29.71
    29.7    29.4      29    29.2    30.1    33.4
    33.4    32.2    30.7    30.3    30.7    30.5      31    30.1    30.5   30.13
   29.43   29.37   29.19   28.64    28.5   28.03   28.04   28.07   27.02   26.73
   22.06   17.94   14.47   14.09   12.93   12.62   12.66   12.91    17.2   20.68
   23.96   26.45    26.7   26.57   27.68   27.61   27.56   27.55   27.32   27.73
   27.92   27.86   27.85   27.76   27.75   28.05   28.66    29.4    29.9    29.7
    29.7    29.4      29    29.2    30.1    33.4
  4085.7  4085.8  4275.8  4295.8  4315.8  4325.8  4365.8  4445.8  4621.2  4671.2
  4763.9  4764.8  4777.1  4813.7  4825.9  4867.2  4877.4  4917.4  4967.1  4973.3
  4979.8  4986.3    4992  4993.5  4998.1  4998.2  5000.1  5001.9  5006.9  5014.6
  5021.4  5026.2  5029.6  5030.4  5031.1  5034.6  5036.8  5037.3  5048.5  5068.8
  5078.5  5124.2  5130.8  5180.1  5182.9  5235.1  5250.7  5269.8  5289.8  5477.8
  5481.4  5561.4  5591.4  5621.4  5900.8  5900.9
    33.4    32.2    30.7    30.3    30.7    30.5      31    30.1    30.5    30.2
   29.44   29.38    29.2   28.96    28.9   28.41   28.29   28.08   27.03   26.74
   26.21   26.08   25.96   25.93   25.94   25.94   25.94   25.95   25.96   25.98
   25.99   26.46   26.71   26.58   27.69   27.62   27.57   27.85   27.87   27.91
   27.93   27.87   27.86   27.94   27.95   28.13   28.67   29.41   29.91   29.71
    29.7    29.4      29    29.2    30.1    33.4
   28.32   27.12   25.62   25.22   25.62   25.42   25.92   25.02   25.42   25.05
   24.35   24.29   24.11   23.56   23.42   22.95   22.96   22.99   21.94   21.65
   16.98   12.86    9.39    9.01    7.85    7.54    7.58    7.83   12.12    15.6
   18.88   21.37   21.62   21.49    22.6   22.53   22.48   22.47   22.24   22.65
   22.84   22.78   22.77   22.68   22.67   22.97   23.58   24.32   24.82   24.62
   24.62   24.32   23.92   24.12   25.02   28.32
BR Coef= 1 , 0 , 0 ,1.25, 0 ,,,0.8,-1,2,0,
WSPro=,,,, 1 ,,,, 0 ,,,, 0 ,,,,-1 ,-1 ,-1 , 0 , 0 , 0 , 0 , 0
Culvert=1,10,,772,0.024,0.8,1,1,3,11.11,5000,7.67,5000,Culvert #1  , 0 ,10
Culvert Bottom n=0.024
BR U #Sta/Elev= 56
  4085.7    33.4  4085.8    32.2  4275.8    30.7  4295.8    30.3  4315.8    30.7
  4325.8    30.5  4365.8      31  4445.8    30.1  4621.2    30.5  4671.2   30.13
  4763.9   29.43  4764.8   29.37  4777.1   29.19  4813.7   28.64  4825.9    28.5
  4867.2   28.03  4877.4   28.04  4917.4   28.07  4967.1   27.02  4973.3   26.73
  4979.8   22.06  4986.3   17.94    4992   14.47  4993.5   14.09  4998.1   12.93
  4998.2   12.62  5000.1   12.66  5001.9   12.91  5006.9    17.2  5014.6   20.68
  5021.4   23.96  5026.2   26.45  5029.6    26.7  5030.4   26.57  5031.1   27.68
  5034.6   27.61  5036.8   27.56  5037.3   27.55  5048.5   27.32  5068.8   27.73
  5078.5   27.92  5124.2   27.86  5130.8   27.85  5180.1   27.76  5182.9   27.75
  5235.1   28.05  5250.7   28.66  5269.8    29.4  5289.8    29.9  5477.8    29.7
  5481.4    29.7  5561.4    29.4  5591.4      29  5621.4    29.2  5900.8    30.1
  5900.9    33.4
BR U #Mann= 5
  4085.7      .2  4671.2      .1  4973.3    .045  5026.2      .1  5477.8      .2
BR U Banks=4973.3,5026.2
BR D #Sta/Elev= 56
  4085.7   28.32  4085.8   27.12  4275.8   25.62  4295.8   25.22  4315.8   25.62
  4325.8   25.42  4365.8   25.92  4445.8   25.02  4621.2   25.42  4671.2   25.05
  4763.9   24.35  4764.8   24.29  4777.1   24.11  4813.7   23.56  4825.9   23.42
  4867.2   22.95  4877.4   22.96  4917.4   22.99  4967.1   21.94  4973.3   21.65
  4979.8   16.98  4986.3   12.86    4992    9.39  4993.5    9.01  4998.1    7.85
  4998.2    7.54  5000.1    7.58  5001.9    7.83  5006.9   12.12  5014.6    15.6
  5021.4   18.88  5026.2   21.37  5029.6   21.62  5030.4   21.49  5031.1    22.6
  5034.6   22.53  5036.8   22.48  5037.3   22.47  5048.5   22.24  5068.8   22.65
  5078.5   22.84  5124.2   22.78  5130.8   22.77  5180.1   22.68  5182.9   22.67
  5235.1   22.97  5250.7   23.58  5269.8   24.32  5289.8   24.82  5477.8   24.62
  5481.4   24.62  5561.4   24.32  5591.4   23.92  5621.4   24.12  5900.8   25.02
  5900.9   28.32
BR D #Mann= 5
  4085.7      .2  4671.2      .1  4973.3    .045  5026.2      .1  5477.8      .2
BR D Banks=4973.3,5026.2
BC Design=,, 0 ,, 0 ,,,,,,
BC HTab HWMax=33.4
BC Use User HTab Curves=0
BC User HTab FreeFlow(D)= 0