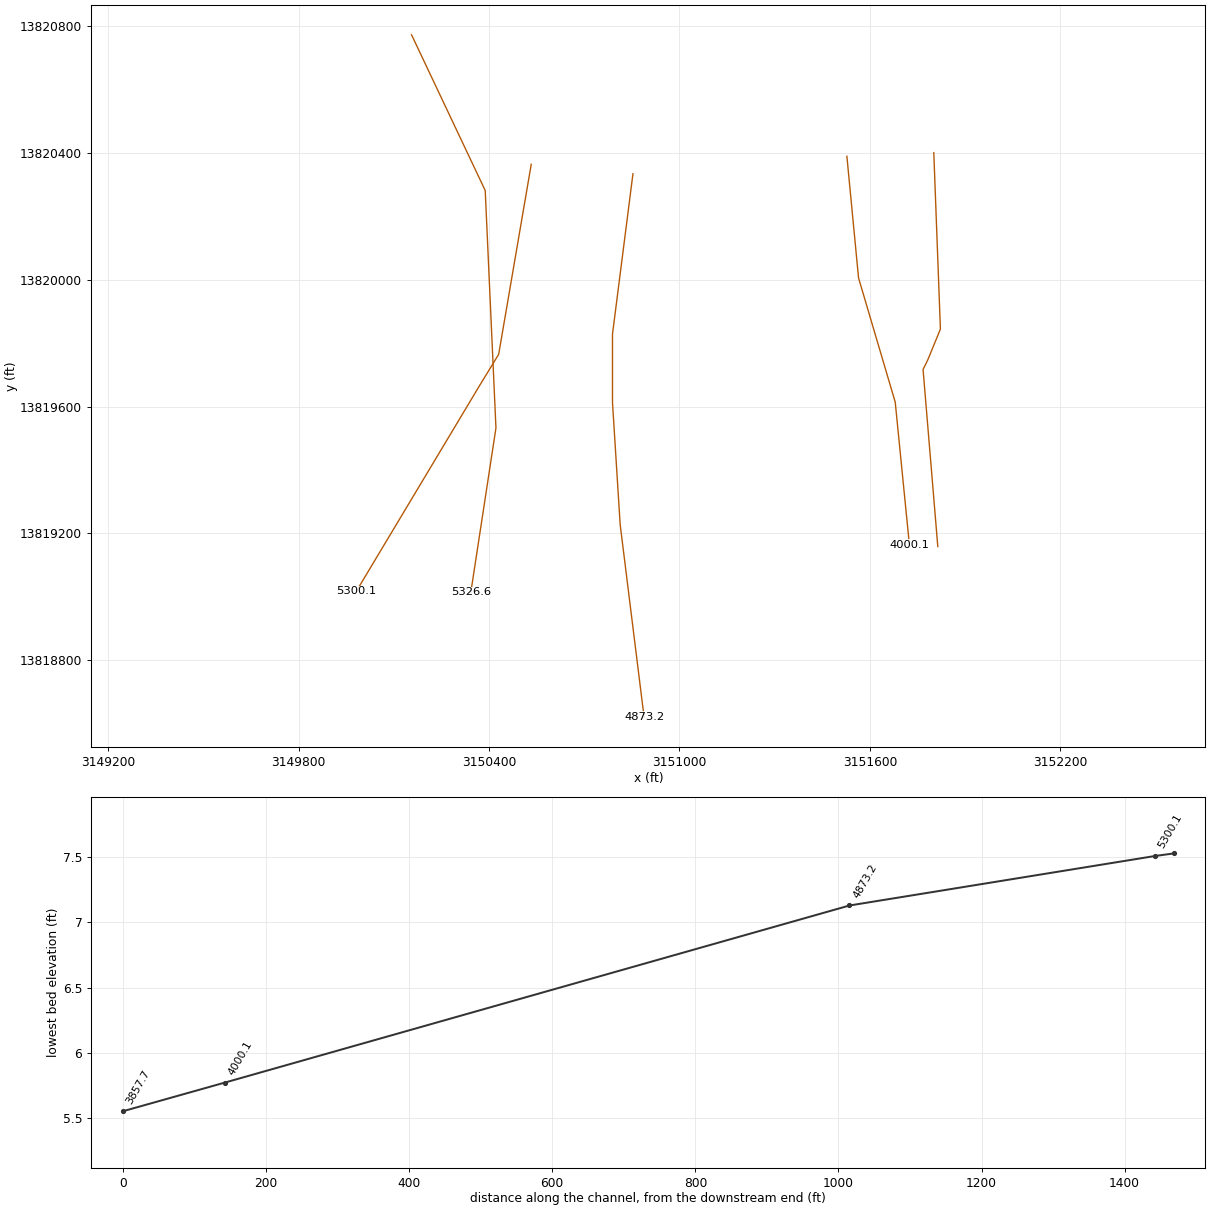
HEC-RAS study C103-00-00.PRJ: C103-00-00

--- C103-00-00.g01 (geometry) --- (continued)

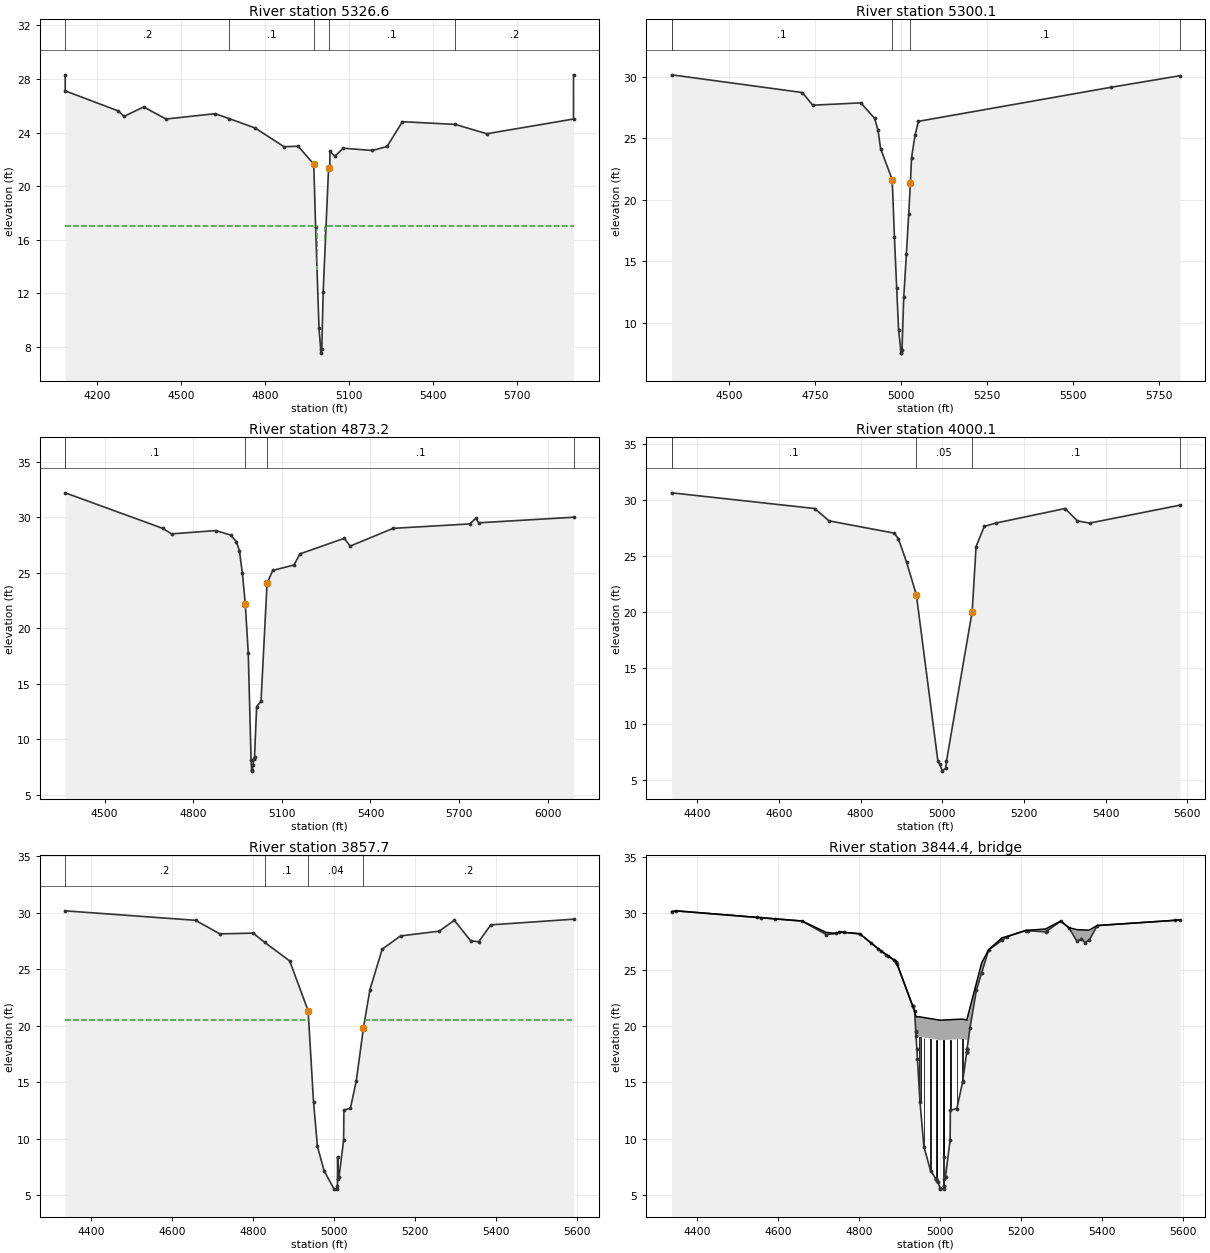
Type RM Length L Ch R = 1 ,5326.6  ,26.5,26.5,26.5
BEGIN DESCRIPTION:
Downstream Section of Bridge/Culvert/Weir
END DESCRIPTION:
XS GIS Cut Line= 4
      3150155.93     13820771.14       3150388.1     13820280.42
      3150421.91     13819532.32      3150342.81     13819014.87
#Sta/Elev= 30
  4085.7   28.31  4085.8   27.11  4275.8   25.61  4295.8   25.21  4365.8   25.91
  4445.8   25.01  4621.2   25.41  4671.2   25.04  4763.9   24.34  4867.2   22.94
  4917.4   22.98  4973.3   21.64  4979.8   16.97    4992    9.38  4998.1    7.84
  4998.2    7.53  5001.9    7.82  5006.9   12.11  5026.2   21.36  5030.4   21.48
  5031.1   22.59  5048.5   22.23  5078.5   22.83  5182.9   22.66  5235.1   22.96
  5289.8   24.81  5477.8   24.61  5591.4   23.91  5900.8   25.01  5900.9   28.31
#Mann= 5 , 1 , 0
  4085.7      .2       0  4671.2      .1       0  4973.3    .045       0
  5026.2      .1       0  5477.8      .2       0
#XS Ineff= 2 , 0
       0    4985      17    5015       0      17
Permanent Ineff=
       F       F
Bank Sta=4973.3,5026.2
XS Rating Curve= 0 ,0
Exp/Cntr=0.5,0.3

Type RM Length L Ch R = 1 ,5300.1  ,403.9,426.9,437
BEGIN DESCRIPTION:
Cross Section 5300.1-Interpolated
END DESCRIPTION:
XS GIS Cut Line= 4
      3150533.11     13820363.11       3150430.5     13819764.43
      3150372.87     13819670.12       3149982.3     13819018.33
#Sta/Elev= 24
  4332.2   30.14  4712.2    28.7  4742.2   27.67  4882.2   27.86  4922.2    26.6
  4932.2   25.62  4939.6   24.14  4973.3   21.62  4979.8   16.95  4986.3   12.83
    4992    9.36  4998.1    7.82  4998.2    7.51  5000.1    7.55  5001.9     7.8
  5006.9   12.09  5014.6   15.57  5021.4   18.85  5026.2   21.34  5029.6   23.41
  5039.6   25.21  5049.6   26.36  5610.1   29.13    5810   30.07
#Mann= 5 , 1 , 0
  4332.2      .2       0  4332.2      .1       0  4973.3     .05       0
  5026.2      .1       0    5810      .2       0
Bank Sta=4973.3,5026.2
XS Rating Curve= 0 ,0
Exp/Cntr=0.3,0.1

Type RM Length L Ch R = 1 ,4873.2  ,853,873.1,922
BEGIN DESCRIPTION:
Cross Section 4873.2
END DESCRIPTION:
XS GIS Cut Line= 5
      3150853.56     13820333.24      3150789.04      13819827.8
      3150789.04     13819612.71      3150813.23     13819228.25
      3150888.51     13818621.97
#Sta/Elev= 29
  4366.6    32.2  4696.6      29  4726.6    28.5  4876.2    28.8  4926.2    28.4
  4946.2    27.8  4956.2      27  4966.2      25  4976.2    22.2  4986.2    17.8
  4995.8    8.16  4997.7    7.13  5000.3    7.22  5002.7    7.71  5004.2    8.21
  5007.4    8.36  5014.7   12.94  5029.5   13.43  5049.9   24.04  5069.1   25.21
  5141.2    25.7  5161.2    26.7  5311.2    28.1  5331.2    27.4  5476.5      29
  5736.5    29.4  5756.5    29.9  5766.5    29.5  6087.4      30
#Mann= 5 , 1 , 0
  4366.6      .2       0  4366.6      .1       0  4976.2     .05       0
  5049.9      .1       0  6087.4      .2       0
Bank Sta=4976.2,5049.9
XS Rating Curve= 0 ,0
Exp/Cntr=0.3,0.1

Type RM Length L Ch R = 1 ,4000.1  ,172.8,142.4,95.6
BEGIN DESCRIPTION:
Cross Section 4000.1-Interpolated
END DESCRIPTION:
XS GIS Cut Line= 4
      3151527.51     13820388.39      3151564.27     13820005.02
       3151679.8     13819613.77      3151724.44     13819164.75
#Sta/Elev= 20
  4337.7    30.6  4687.7    29.2  4722.8    28.1  4882.8      27  4892.8    26.5
  4912.8    24.4  4936.6   21.51  4989.5    6.63  4994.4    6.37  5000.1    5.77
  5008.7    6.05  5010.4    6.66  5073.3   20.01  5082.8    25.8  5102.8    27.6
  5130.8    27.9  5300.8    29.2  5330.8    28.1  5360.8    27.9    5582    29.5
#Mann= 5 , 1 , 0
  4337.7      .2       0  4337.7      .1       0  4936.6     .05       0
  5073.3      .1       0    5582      .2       0
Bank Sta=4936.6,5073.3
XS Rating Curve= 0 ,0
Exp/Cntr=0.5,0.3

Type RM Length L Ch R = 1 ,3857.7  ,26.6,26.6,26.6
BEGIN DESCRIPTION:
Upstream Section of Bridge/Culvert/Weir
END DESCRIPTION:
XS GIS Cut Line= 5
       3151801.3     13820399.84      3151822.19     13819843.81
      3151781.65     13819745.24       3151767.5     13819716.79
      3151813.94     13819158.69
#Sta/Elev= 30
    4337   30.16  4658.8   29.32  4718.8   28.12  4801.1   28.19  4829.1   27.38
  4891.1   25.73  4936.6   21.33    4950   13.25  4959.6    9.32    4976    7.19
  5000.1    5.59  5008.5    5.55    5009    5.82  5009.5    8.42  5010.4    6.48
    5013    6.65  5024.3    9.91    5025   12.54    5041    12.7  5055.3   15.07
  5073.3   19.83  5089.3    23.2  5119.5   26.77  5164.7   27.94    5260   28.36
  5297.6   29.32  5337.6   27.52  5357.6   27.42  5387.6   28.92  5591.8   29.42
#Mann= 4 , 1 , 0
    4337      .2       0  4829.1      .1       0  4936.6     .04       0
  5073.3      .2       0
#XS Ineff= 2 , 0
       0    4938    20.5    5076       0    20.5
Permanent Ineff=
       F       F
Bank Sta=4936.6,5073.3
XS Rating Curve= 0 ,0
Exp/Cntr=0.5,0.3

Type RM Length L Ch R = 3 ,3844.4  ,,,
BEGIN DESCRIPTION:
IOLA ROAD
Structure ID: C03-3
END DESCRIPTION:
Bridge Culvert--1,0,-1,-1, 0
Deck Dist Width WeirC Skew NumUp NumDn MinLoCord MaxHiCord MaxSubmerge Is_Ogee
10,6.6,2.6,0, 35, 35, , , 0.95, 0, 1,1,,
    4337  4348.8  4658.8  4718.8  4743.7  4750.8  4801.1  4854.9  4891.1  4936.6
 4939.51  4940.2  4942.2  4943.6  4999.3  5055.3 5065.41 5066.29  5066.4  5073.3
  5089.3  5102.4  5119.5  5152.5  5164.7  5210.7    5260  5297.6  5317.6  5337.6
  5347.6  5357.6  5367.6  5387.6  5591.8
   30.14   30.21   29.31   28.29   28.21   28.34   28.18   26.62   25.72   21.32
    20.9   20.87   20.78   20.84   20.51   20.61   20.52   20.64   20.66   21.61
   23.81   25.61   26.76   27.82   27.93   28.47    28.6   29.31   28.71   28.54
   28.53   28.51    28.5   28.91    29.4
   30.14    30.2    29.3    28.1    28.2   28.33   28.17   26.61   25.71   21.31
   19.56   19.14   19.01   19.07   18.74   18.84   18.75   18.87   17.99   19.81
   23.18   24.73   26.75    27.6   27.92   28.46   28.34    29.3    28.7    27.5
    27.7    27.4    27.6    28.9    29.4
    4337  4348.8  4658.8  4718.8  4743.7  4750.8  4801.1  4854.9  4891.1  4936.6
 4939.51  4940.2  4942.2  4943.6  4999.3  5055.3 5065.41 5066.29  5066.4  5073.3
  5089.3  5102.4  5119.5  5152.5  5164.7  5210.7    5260  5297.6  5317.6  5337.6
  5347.6  5357.6  5367.6  5387.6  5591.8
   30.14   30.21   29.31   28.29   28.21   28.34   28.18   26.62   25.72   21.32
    20.9   20.87   20.78   20.84   20.51   20.61   20.52   20.64   20.66   21.61
   23.81   25.61   26.76   27.82   27.93   28.47    28.6   29.31   28.71   28.54
   28.53   28.51    28.5   28.91    29.4
   30.11   30.17   29.27   28.07   28.17    28.3   28.14   26.58   25.68   21.28
   19.53   19.11   18.98   19.04   18.71   18.81   18.72   18.84   17.96   19.78
   23.15    24.7   26.72   27.57   27.89   28.43   28.31   29.27   28.67   27.47
   27.67   27.37   27.57   28.87   29.37
Pier Skew, UpSta & Num, DnSta & Num=  ,4950, 2 ,4950, 2 , 0 , 0 , 0 ,,
     5.4     5.4
   11.12   20.05
     5.4     5.4
   11.09   20.02
Pier Skew, UpSta & Num, DnSta & Num=  ,4959.6, 2 ,4959.6, 2 , 0 , 0 , 0 ,,
     1.5     1.5
     8.2   19.98
     1.5     1.5
    8.17   19.95
Pier Skew, UpSta & Num, DnSta & Num=  ,4976, 2 ,4976, 2 , 0 , 0 , 0 ,,
     1.5     1.5
    6.13   19.88
     1.5     1.5
     6.1   19.85
Pier Skew, UpSta & Num, DnSta & Num=  ,4990.6, 2 ,4990.6, 2 , 0 , 0 , 0 ,,
       1       1
    5.36   19.79
       1       1
    5.33   19.76
Pier Skew, UpSta & Num, DnSta & Num=  ,4991.7, 2 ,4991.7, 2 , 0 , 0 , 0 ,,
       1       1
    5.27   19.79
       1       1
    5.24   19.76
Pier Skew, UpSta & Num, DnSta & Num=  ,5006.9, 2 ,5006.9, 2 , 0 , 0 , 0 ,,
       1       1
    4.54   19.76
       1       1
    4.51   19.73
Pier Skew, UpSta & Num, DnSta & Num=  ,5008.4, 2 ,5008.4, 2 , 0 , 0 , 0 ,,
     1.5     1.5
    4.53   19.76
     1.5     1.5
     4.5   19.73
Pier Skew, UpSta & Num, DnSta & Num=  ,5009.9, 2 ,5009.9, 2 , 0 , 0 , 0 ,,
       1       1
    5.46   19.76
       1       1
    5.43   19.73
Pier Skew, UpSta & Num, DnSta & Num=  ,5023.5, 2 ,5023.5, 2 , 0 , 0 , 0 ,,
       1       1
    8.51   19.78
       1       1
    8.48   19.75
Pier Skew, UpSta & Num, DnSta & Num=  ,5025, 2 ,5025, 2 , 0 , 0 , 0 ,,
       1       1
    9.64   19.79
       1       1
    9.61   19.76
Pier Skew, UpSta & Num, DnSta & Num=  ,5041, 2 ,5041, 2 , 0 , 0 , 0 ,,
       1       1
   11.67   19.81
       1       1
   11.64   19.78
Pier Skew, UpSta & Num, DnSta & Num=  ,5055.2, 2 ,5055.2, 2 , 0 , 0 , 0 ,,
       1       1
   13.95   19.84
       1       1
   13.92   19.81
BR Coef= 1 , 1 , 0 ,1.25, 0 ,,,0.8,0,2,0,
WSPro=,,,, 1 ,,,, 0 ,,,, 0 ,,,,-1 ,-1 ,-1 , 0 , 0 , 0 , 0 , 0
BR U #Sta/Elev= 75
    4337   30.14  4348.8    30.2    4547   29.62    4557    29.6    4592   29.49
  4658.8    29.3  4718.8    28.1  4743.7    28.2  4750.8   28.33    4762   28.29
  4801.1   28.17  4829.1   27.36    4847   26.84  4854.9   26.61    4867   26.31
    4872   26.18    4887   25.81  4891.1   25.71  4891.2    25.7  4893.7   25.46
 4931.89   21.77    4932   21.75 4932.11   21.74  4936.6   21.31 4939.51   19.56
  4939.6    19.5  4940.2   19.14  4942.2   17.93  4943.6   17.09    4950   13.23
  4959.6     9.3    4976    7.17  4989.5    6.43  4989.6    6.43  4990.6    6.42
  4991.7    6.29  4994.4    6.17  4999.3    5.65  5000.1    5.57  5008.5    5.53
  5008.7    5.85    5009     5.8  5009.5     8.4  5010.4    6.46    5013    6.63
  5024.3    9.89    5025   12.52    5041   12.68  5055.3   15.05  5055.7   15.16
 5065.19   17.67  5065.3   17.69 5065.41   17.72  5066.2   17.93 5066.29   17.96
  5066.4   17.99  5073.3   19.81  5089.3   23.18  5102.4   24.73  5119.5   26.75
  5152.5    27.6  5164.7   27.92  5210.7   28.46  5215.9   28.45    5260   28.34
  5262.6   28.41  5297.6    29.3  5317.6    28.7  5337.6    27.5  5347.6    27.7
  5357.6    27.4  5367.6    27.6  5387.6    28.9  5580.6   29.37  5591.8    29.4
BR U #Mann= 4
    4337      .2  4829.1      .1  4936.6     .04  5073.3      .2
BR U Banks=4936.6,5073.3
BR D #Sta/Elev= 75
    4337   30.11  4348.8   30.17    4547   29.59    4557   29.57    4592   29.46
  4658.8   29.27  4718.8   28.07  4743.7   28.17  4750.8    28.3    4762   28.26
  4801.1   28.14  4829.1   27.33    4847   26.81  4854.9   26.58    4867   26.28
    4872   26.15    4887   25.78  4891.1   25.68  4891.2   25.67  4893.7   25.43
 4931.89   21.74    4932   21.72 4932.11   21.71  4936.6   21.28 4939.51   19.53
  4939.6   19.47  4940.2   19.11  4942.2    17.9  4943.6   17.06    4950    13.2
  4959.6    9.27    4976    7.14  4989.5     6.4  4989.6     6.4  4990.6    6.39
  4991.7    6.26  4994.4    6.14  4999.3    5.62  5000.1    5.54  5008.5     5.5
  5008.7    5.82    5009    5.77  5009.5    8.37  5010.4    6.43    5013     6.6
  5024.3    9.86    5025   12.49    5041   12.65  5055.3   15.02  5055.7   15.13
 5065.19   17.64  5065.3   17.66 5065.41   17.69  5066.2    17.9 5066.29   17.93
  5066.4   17.96  5073.3   19.78  5089.3   23.15  5102.4    24.7  5119.5   26.72
  5152.5   27.57  5164.7   27.89  5210.7   28.43  5215.9   28.42    5260   28.31
  5262.6   28.38  5297.6   29.27  5317.6   28.67  5337.6   27.47  5347.6   27.67
  5357.6   27.37  5367.6   27.57  5387.6   28.87  5580.6   29.34  5591.8   29.37
BR D #Mann= 4
    4337      .2  4829.1      .1  4936.6     .04  5073.3      .2
BR D Banks=4936.6,5073.3
BC Design=,, 0 ,, 0 ,,,,,,
BC HTab HWMax=30.22
BC Use User HTab Curves=0
BC User HTab FreeFlow(D)= 0