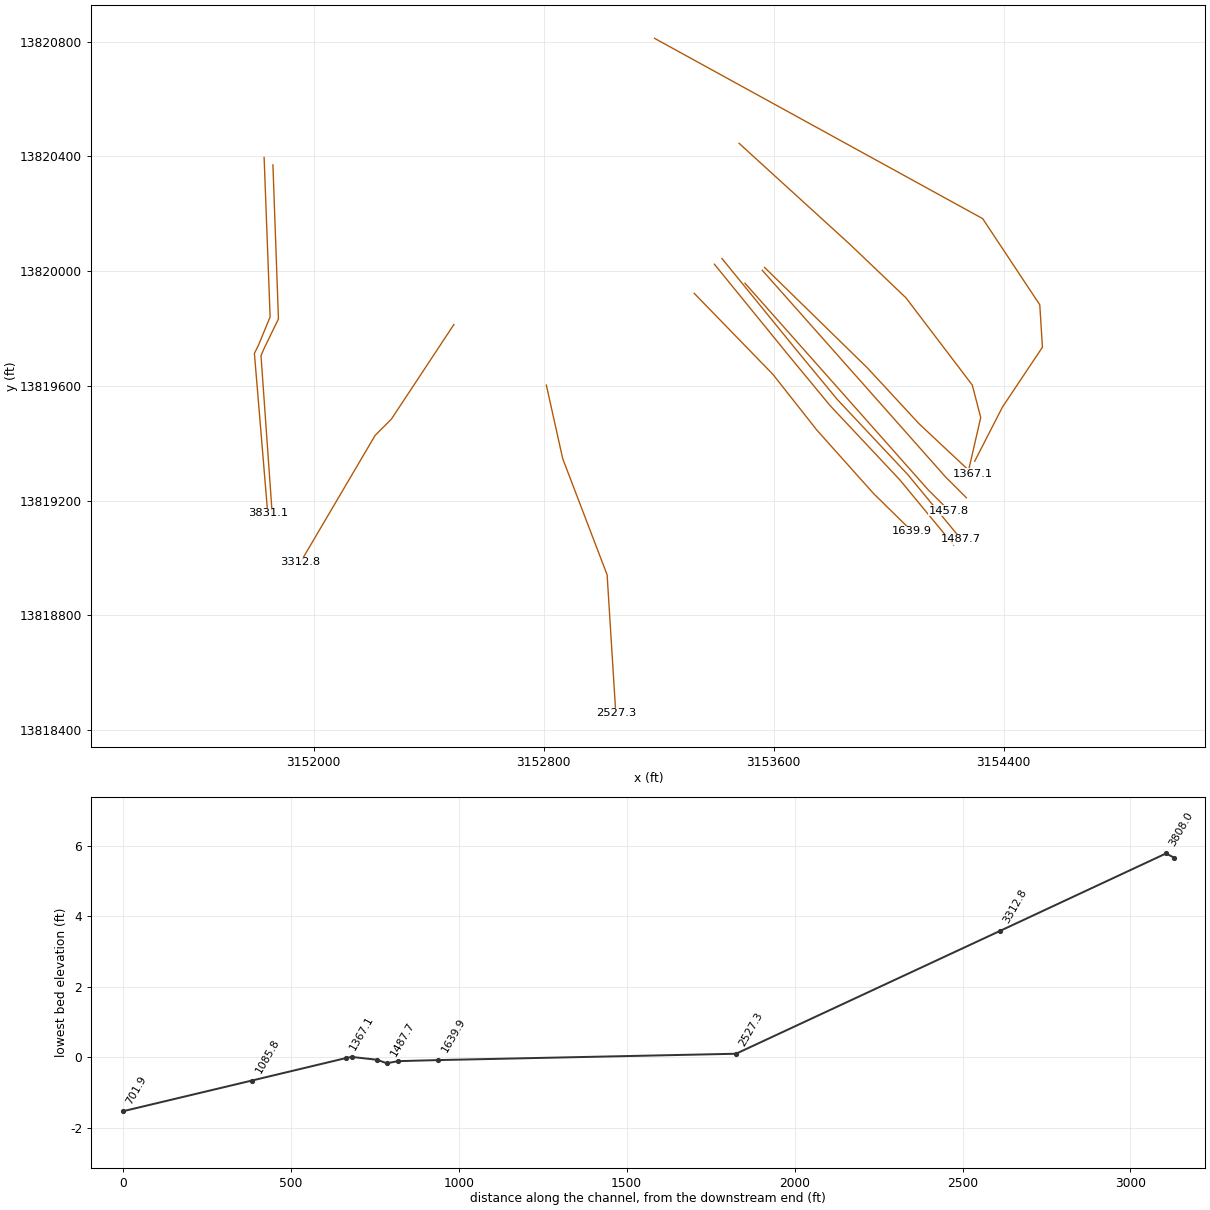
HEC-RAS study C103-00-00.PRJ: C103-00-00

--- C103-00-00.g01 (geometry) --- (continued)

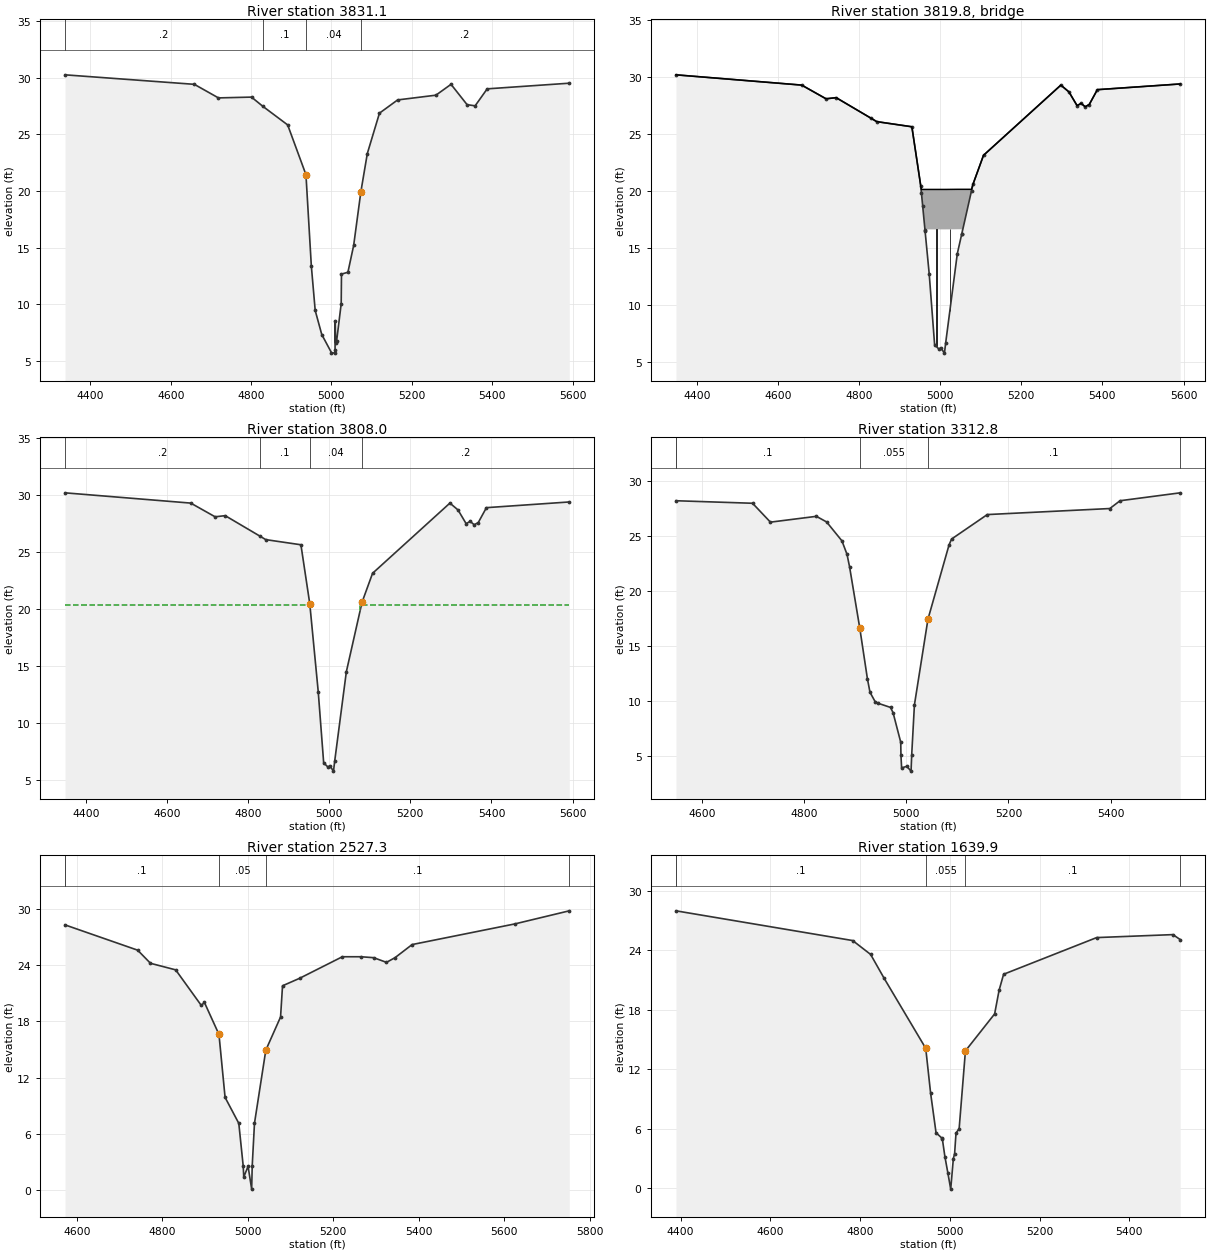
Type RM Length L Ch R = 1 ,3831.1  ,23.1,23.1,23.1
BEGIN DESCRIPTION:
Downstream Section of Bridge/Culvert/Weir
END DESCRIPTION:
XS GIS Cut Line= 5
      3151827.67     13820396.38      3151848.57     13819840.35
      3151808.03     13819741.78      3151793.88     13819713.33
      3151840.31     13819155.24
#Sta/Elev= 30
    4337   30.27  4658.8   29.43  4718.8   28.23  4801.1    28.3  4829.1   27.49
  4891.1   25.84  4936.6   21.44    4950   13.36  4959.6    9.43    4976     7.3
  5000.1     5.7  5008.5    5.66    5009    5.93  5009.5    8.53  5010.4    6.59
    5013    6.76  5024.3   10.02    5025   12.65    5041   12.81  5055.3   15.18
  5073.3   19.94  5089.3   23.31  5119.5   26.88  5164.7   28.05    5260   28.47
  5297.6   29.43  5337.6   27.63  5357.6   27.53  5387.6   29.03  5591.8   29.53
#Mann= 4 , 1 , 0
    4337      .2       0  4829.1      .1       0  4936.6     .04       0
  5073.3      .2       0
#XS Ineff= 2 , 0
       0    4938    20.3    5076       0    20.3
Permanent Ineff=
       F       F
Bank Sta=4936.6,5073.3
XS Rating Curve= 0 ,0
Exp/Cntr=0.5,0.3

Type RM Length L Ch R = 3 ,3819.8  ,,,
BEGIN DESCRIPTION:
42" PIPELINE
END DESCRIPTION:
Bridge Culvert--1,0,-1,-1, 0
Deck Dist Width WeirC Skew NumUp NumDn MinLoCord MaxHiCord MaxSubmerge Is_Ogee
10,3.6,2.6,0, 32, 32, , , 0.95, 0, 1,1,,
  4348.8  4658.8  4718.8  4743.7  4829.1  4843.7 4930.35 4952.15 4953.85 4956.95
 4962.76 4962.85 4973.05 4986.45 4997.55 5001.45 5010.65 5013.55 5042.35 5053.24
 5053.35 5077.35 5080.95 5106.95  5297.6  5317.6  5337.6  5347.6  5357.6  5367.6
  5387.6  5591.8
    30.2    29.3    28.1    28.2   26.41    26.1   25.65   20.49   20.16   20.16
   20.16   20.16   20.16   20.16   20.16   20.16   20.16   20.16   20.17   20.17
   20.17   20.17   20.61   23.15    29.3    28.7    27.5    27.7    27.4    27.6
    28.9    29.4
    30.2    29.3    28.1    28.2   26.41    26.1   25.65   20.49   19.86   18.72
   16.57   16.66   16.66   16.66   16.66   16.66   16.66   16.66   16.67   16.67
   16.26   20.04   20.61   23.15    29.3    28.7    27.5    27.7    27.4    27.6
    28.9    29.4
  4348.8  4658.8  4718.8  4743.7  4829.1  4843.7 4930.35 4952.15 4953.85 4956.95
 4962.76 4962.85 4973.05 4986.45 4997.55 5001.45 5010.65 5013.55 5042.35 5053.24
 5053.35 5077.35 5080.95 5106.95  5297.6  5317.6  5337.6  5347.6  5357.6  5367.6
  5387.6  5591.8
    30.2    29.3    28.1    28.2   26.41    26.1   25.65   20.49   20.16   20.16
   20.16   20.16   20.16   20.16   20.16   20.16   20.16   20.16   20.17   20.17
   20.17   20.17   20.61   23.15    29.3    28.7    27.5    27.7    27.4    27.6
    28.9    29.4
    30.2    29.3    28.1    28.2   26.41    26.1   25.65   20.49   19.86   18.72
   16.57   16.66   16.66   16.66   16.66   16.66   16.66   16.66   16.67   16.67
   16.26   20.04   20.61   23.15    29.3    28.7    27.5    27.7    27.4    27.6
    28.9    29.4
Pier Skew, UpSta & Num, DnSta & Num=  ,4990.4, 2 ,4990.4, 2 , 0 , 0 , 0 ,,
     1.4     1.4
    5.38   17.66
     1.4     1.4
    5.38   17.66
Pier Skew, UpSta & Num, DnSta & Num=  ,5023.8, 2 ,5023.8, 2 , 0 , 0 , 0 ,,
     1.4     1.4
    8.27   17.66
     1.4     1.4
    8.27   17.66
BR Coef= 1 , 1 , 0 ,1.25, 0 ,,,0.8,0,2,0,
WSPro=,,,, 1 ,,,, 0 ,,,, 0 ,,,,-1 ,-1 ,-1 , 0 , 0 , 0 , 0 , 0
BR U #Sta/Elev= 32
  4348.8    30.2  4658.8    29.3  4718.8    28.1  4743.7    28.2  4829.1   26.41
  4843.7    26.1 4930.35   25.65 4952.15   20.49 4953.85   19.86 4956.95   18.72
 4962.76   16.57 4962.85   16.54 4973.05   12.77 4986.45    6.54 4997.55    6.16
 5001.45    6.29 5010.65    5.82 5013.55    6.68 5042.35   14.53 5053.24   16.25
 5053.35   16.26 5077.35   20.04 5080.95   20.61 5106.95   23.15  5297.6    29.3
  5317.6    28.7  5337.6    27.5  5347.6    27.7  5357.6    27.4  5367.6    27.6
  5387.6    28.9  5591.8    29.4
BR U #Mann= 4
  4348.8      .2  4829.1      .1 4952.15     .04 5080.95      .2
BR U Banks=4952.15,5080.95
BR D #Sta/Elev= 32
  4348.8    30.2  4658.8    29.3  4718.8    28.1  4743.7    28.2  4829.1   26.41
  4843.7    26.1 4930.35   25.65 4952.15   20.49 4953.85   19.86 4956.95   18.72
 4962.76   16.57 4962.85   16.54 4973.05   12.77 4986.45    6.54 4997.55    6.16
 5001.45    6.29 5010.65    5.82 5013.55    6.68 5042.35   14.53 5053.24   16.25
 5053.35   16.26 5077.35   20.04 5080.95   20.61 5106.95   23.15  5297.6    29.3
  5317.6    28.7  5337.6    27.5  5347.6    27.7  5357.6    27.4  5367.6    27.6
  5387.6    28.9  5591.8    29.4
BR D #Mann= 4
  4348.8      .2  4829.1      .1 4952.15     .04 5080.95      .2
BR D Banks=4952.15,5080.95
BC Design=,, 0 ,, 0 ,,,,,,
BC HTab HWMax=30.33
BC Use User HTab Curves=0
BC User HTab FreeFlow(D)= 0

Type RM Length L Ch R = 1 ,3808.0  ,495.2,495.2,495.2
BEGIN DESCRIPTION:
Downstream Section of Bridge/Culvert/Weir
END DESCRIPTION:
XS GIS Cut Line= 5
       3151858.3     13820370.34      3151877.53     13819833.51
      3151827.78     13819730.91      3151816.87     13819705.32
       3151856.6     13819142.74
#Sta/Elev= 25
  4348.8   30.16  4658.8   29.26  4718.8   28.06  4743.7   28.16  4829.1   26.37
  4843.7   26.06 4930.35   25.61 4952.15   20.45 4973.05   12.73 4986.45     6.5
 4997.55    6.12 5001.45    6.25 5010.65    5.78 5013.55    6.64 5042.35   14.49
 5080.95   20.57 5106.95   23.11  5297.6   29.26  5317.6   28.66  5337.6   27.46
  5347.6   27.66  5357.6   27.36  5367.6   27.56  5387.6   28.86  5591.8   29.36
#Mann= 4 , 1 , 0
  4348.8      .2       0  4829.1      .1       0 4952.15     .04       0
 5080.95      .2       0
#XS Ineff= 2 , 0
       0    4953    20.3    5076       0    20.3
Permanent Ineff=
       F       F
Bank Sta=4952.15,5080.95
XS Rating Curve= 0 ,0
Exp/Cntr=0.5,0.3

Type RM Length L Ch R = 1 ,3312.8  ,703.9,785.5,857.8
BEGIN DESCRIPTION:
Cross Section 3312.8-Interpolated
Located At: US GALVESTON ROAD
END DESCRIPTION:
XS GIS Cut Line= 4
      3152487.76     13819813.83      3152270.15      13819483.9
      3152213.99     13819427.74      3151954.25     13818985.48
#Sta/Elev= 29
  4548.8    28.2  4698.8   27.97  4733.8   26.25  4823.8   26.78  4843.8   26.27
  4873.8   24.55  4883.8   23.32  4888.8   22.18  4908.8    16.6  4923.8   11.97
  4928.8   10.76  4938.8    9.91    4944    9.77    4969    9.38    4974     8.9
    4989    6.21  4989.4    5.05  4990.7    3.87  5000.8    4.02  5009.2    3.58
  5010.5    5.08  5015.8    9.61  5042.3   17.41  5083.5   24.16  5088.5   24.71
  5158.5   26.94  5398.5   27.49  5418.5    28.2  5536.3   28.92
#Mann= 5 , 1 , 0
  4548.8      .2       0  4548.8      .1       0  4908.8    .055       0
  5042.3      .1       0  5536.3      .2       0
Bank Sta=4908.8,5042.3
XS Rating Curve= 0 ,0
Exp/Cntr=0.3,0.1

Type RM Length L Ch R = 1 ,2527.3  ,880,887.4,905
BEGIN DESCRIPTION:
Cross Section 2527.3
Located At: US GALVESTON ROAD
END DESCRIPTION:
XS GIS Cut Line= 4
      3152809.36     13819602.62      3152866.35     13819346.18
      3153020.77     13818941.41      3153050.94     13818458.57
#Sta/Elev= 27
  4572.5    28.3  4742.5    25.6  4772.5    24.2  4831.4    23.5  4891.4    19.7
  4898.6   20.03  4932.7   16.61    4947    9.89  4979.1    7.12  4989.4    2.57
  4990.7    1.39  5000.8    2.54  5009.2      .1  5010.5     2.6  5015.8    7.13
  5042.3   14.93  5076.8   18.47  5081.4    21.8  5121.4    22.6  5221.4    24.9
  5264.6    24.9  5294.6    24.8  5324.6    24.3  5344.6    24.8  5384.6    26.2
  5624.6    28.4  5752.2    29.8
#Mann= 5 , 1 , 0
  4572.5      .2       0  4572.5      .1       0  4932.7     .05       0
  5042.3      .1       0  5752.2      .2       0
Bank Sta=4932.7,5042.3
XS Rating Curve= 0 ,0
Exp/Cntr=0.3,0.1

Type RM Length L Ch R = 1 ,1639.9  ,96.2,119.2,135.6
BEGIN DESCRIPTION:
Cross Section 1639.9-Interpolated
END DESCRIPTION:
XS GIS Cut Line= 5
      3153323.72     13819922.59      3153597.87     13819639.73
      3153750.18     13819446.08      3153948.18     13819224.14
      3154080.91     13819093.59
#Sta/Elev= 23
  4389.7      28  4783.6      25  4823.6    23.6  4853.6    21.2  4946.4   14.13
  4957.3     9.6  4969.4    5.61  4982.1    5.08  4983.4       5  4989.1    3.21
  4995.6    1.59  5002.1    -.08    5008    3.01  5010.8     3.5  5013.9    5.58
  5020.9    6.02  5034.9   13.87    5100    17.6    5110      20    5120    21.6
  5327.4    25.3  5497.4    25.6  5513.6    25.1
#Mann= 5 , 1 , 0
  4389.7      .2       0  4389.7      .1       0  4946.4    .055       0
  5034.9      .1       0  5513.6      .2       0
Bank Sta=4946.4,5034.9
XS Rating Curve= 0 ,0
Exp/Cntr=0.5,0.3

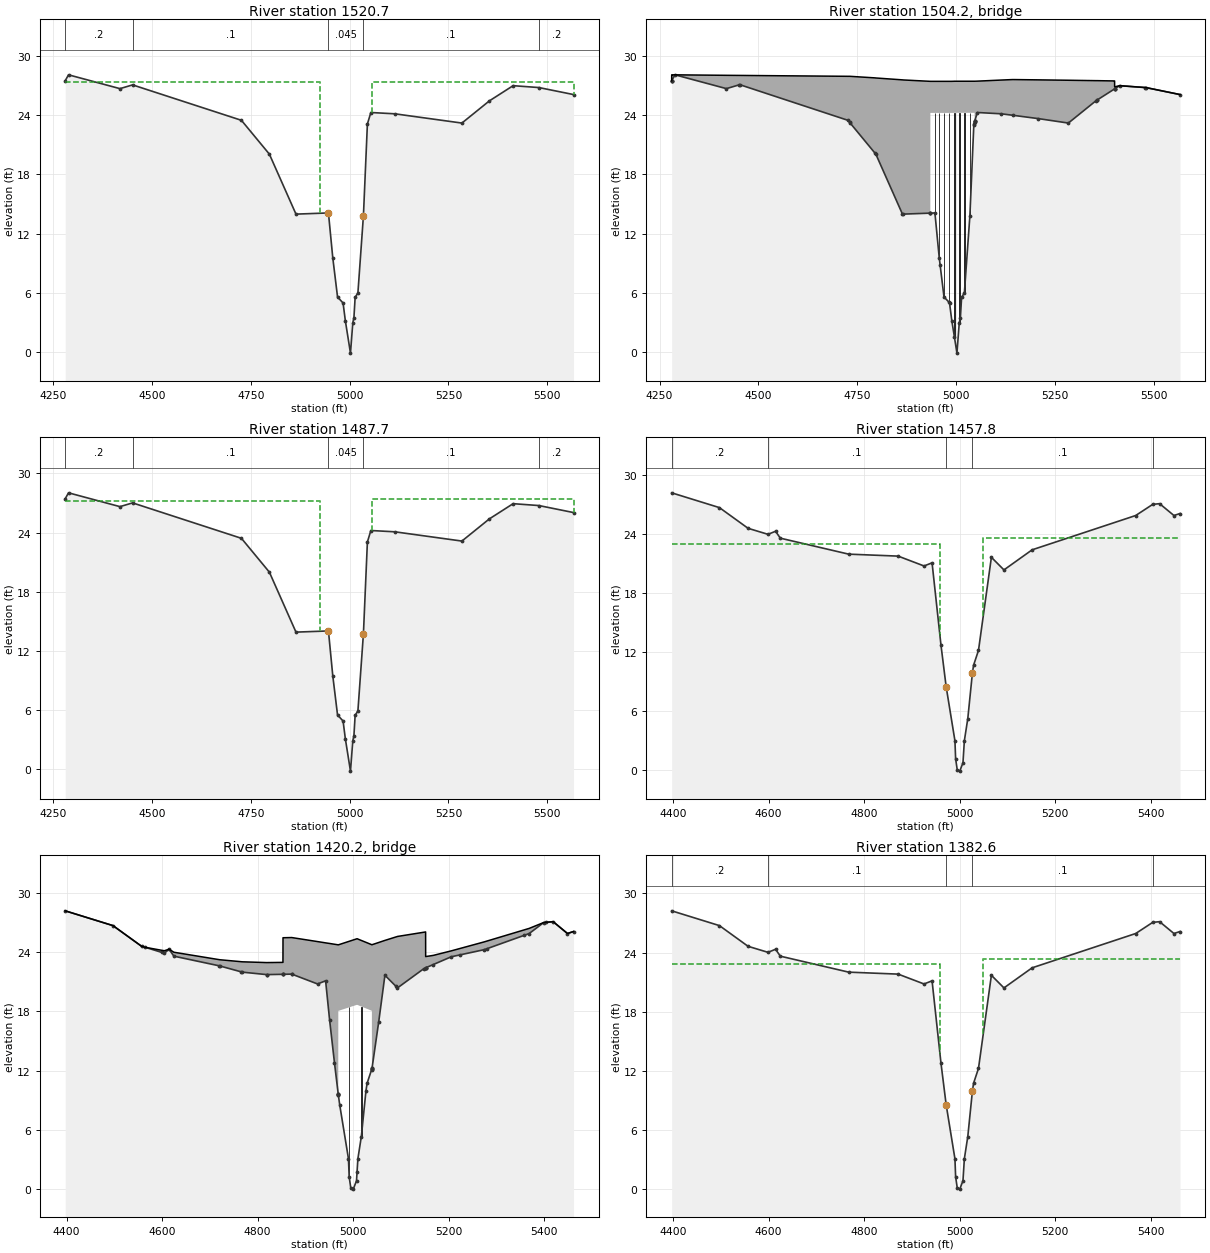
Type RM Length L Ch R = 1 ,1520.7  ,33,33,33
BEGIN DESCRIPTION:
Upstream Section of Bridge/Culvert/Weir
END DESCRIPTION:
XS GIS Cut Line= 5
      3153393.81     13820024.18      3153653.34     13819704.75
      3153796.06     13819531.61      3154039.39     13819271.91
      3154226.09     13819045.22
#Sta/Elev= 26
 4280.69    27.5  4289.1    28.1  4419.1    26.7  4451.1   27.08  4726.3   23.49
    4797   20.06  4864.3   13.98  4946.4    14.1  4957.3    9.57  4969.4    5.58
  4983.4    4.97  4989.1    3.18  5002.1    -.11    5008    2.98  5010.8    3.47
  5013.9    5.55  5020.9    5.99  5034.9   13.84  5044.9   23.12  5053.7   24.28
    5114   24.15  5283.9   23.21  5353.4   25.46  5413.4      27  5478.6   26.81
  5566.2    26.1
#Mann= 5 , 1 , 0
 4280.69      .2       0  4451.1      .1       0  4946.4    .045       0
  5034.9      .1       0  5478.6      .2       0
#XS Ineff= 2 , 0
       0  4924.5    27.4    5057       0    27.4
Permanent Ineff=
       F       F
Bank Sta=4946.4,5034.9
XS Rating Curve= 0 ,0
Exp/Cntr=0.5,0.3

Type RM Length L Ch R = 3 ,1504.2  ,,,
BEGIN DESCRIPTION:
SOUTHERN PACIFIC RAILROAD
Structure ID: C03-2
END DESCRIPTION:
Bridge Culvert--1,0,-1,-1, 0
Deck Dist Width WeirC Skew NumUp NumDn MinLoCord MaxHiCord MaxSubmerge Is_Ogee
10,13,2.6,0, 52, 52, , , 0.95, 0, 1,1,,
 4280.69  4280.8 4280.91  4289.1  4419.1  4451.1  4452.9  4726.3  4730.5  4731.1
  4795.3    4797  4864.3  4866.6  4934.7 4934.81  4934.9  4946.4  4957.3  4959.7
  4969.4  4982.1  4983.4  4989.1  4995.6  5002.1    5008  5010.8  5013.9  5020.9
  5034.9  5044.8  5044.9  5046.7 5046.79  5046.9    5047  5053.7    5114  5143.2
  5208.2  5283.9  5353.4  5356.3  5356.4 5400.69  5400.8 5400.91  5413.4  5478.6
    5481  5566.2
    27.5    28.1    28.1    28.1   28.05   28.04   28.04   27.95   27.95   27.95
   27.79   27.78   27.59   27.58   27.44   27.44   27.44   27.44   27.44   27.44
   27.44   27.44   27.44   27.44   27.45   27.45   27.45   27.45   27.45   27.45
   27.45   27.45   27.45   27.45   27.45   27.45   27.45   27.46   27.57   27.62
   27.59   27.55   27.51   27.51   27.51   27.48   27.48   26.88      27   26.81
    26.8    26.1
    27.5   27.51   27.52    28.1    26.7   27.08    27.1   23.49   23.29   23.26
   20.14   20.06   13.98   13.98   14.08   14.08   24.24   24.24   24.24   24.24
   24.24   24.24   24.24   24.24   24.25   24.25   24.25   24.25   24.25   24.25
   24.25   24.25   24.25   24.25   24.25   23.38    23.4   24.28   24.15      24
   23.66   23.21   25.46   25.53   25.54   26.67   26.68   26.68      27   26.81
    26.8    26.1
 4280.69  4280.8 4280.91  4289.1  4419.1  4451.1  4452.9  4726.3  4730.5  4731.1
  4795.3    4797  4864.3  4866.6  4934.7 4934.81  4934.9  4946.4  4957.3  4959.7
  4969.4  4982.1  4983.4  4989.1  4995.6  5002.1    5008  5010.8  5013.9  5020.9
  5034.9  5044.8  5044.9  5046.7 5046.79  5046.9    5047  5053.7    5114  5143.2
  5208.2  5283.9  5353.4  5356.3  5356.4 5400.69  5400.8 5400.91  5413.4  5478.6
    5481  5566.2
    27.5    28.1    28.1    28.1   28.05   28.04   28.04   27.95   27.95   27.95
   27.79   27.78   27.59   27.58   27.44   27.44   27.44   27.44   27.44   27.44
   27.44   27.44   27.44   27.44   27.45   27.45   27.45   27.45   27.45   27.45
   27.45   27.45   27.45   27.45   27.45   27.45   27.45   27.46   27.57   27.62
   27.59   27.55   27.51   27.51   27.51   27.48   27.48   26.88      27   26.81
    26.8    26.1
    27.4   27.41   27.42      28    26.6   26.98      27   23.39   23.19   23.16
   20.04   19.96   13.88   13.88   13.98   13.98   24.14   24.14   24.14   24.14
   24.14   24.14   24.14   24.14   24.15   24.15   24.15   24.15   24.15   24.15
   24.15   24.15   24.15   24.15   24.15   23.28    23.3   24.18   24.05    23.9
   23.56   23.11   25.36   25.43   25.44   26.57   26.58   26.58    26.9   26.71
    26.7      26
Pier Skew, UpSta & Num, DnSta & Num=  ,4946.4, 2 ,4946.4, 2 , 0 , 0 , 0 ,,
     1.3     1.3
   12.83   25.24
     1.3     1.3
   12.73   25.14
Pier Skew, UpSta & Num, DnSta & Num=  ,4957.3, 2 ,4957.3, 2 , 0 , 0 , 0 ,,
     1.3     1.3
    8.36   25.24
     1.3     1.3
    8.26   25.14
Pier Skew, UpSta & Num, DnSta & Num=  ,4969.4, 2 ,4969.4, 2 , 0 , 0 , 0 ,,
     1.3     1.3
    4.55   25.24
     1.3     1.3
    4.45   25.14
Pier Skew, UpSta & Num, DnSta & Num=  ,4982.1, 2 ,4982.1, 2 , 0 , 0 , 0 ,,
     1.3     1.3
    4.01   25.24
     1.3     1.3
    3.91   25.14
Pier Skew, UpSta & Num, DnSta & Num=  ,4995.6, 2 ,4995.6, 2 , 0 , 0 , 0 ,,
     1.3     1.3
     .39   25.25
     1.3     1.3
     .29   25.15
Pier Skew, UpSta & Num, DnSta & Num=  ,5008, 2 ,5008, 2 , 0 , 0 , 0 ,,
     1.3     1.3
    1.64   25.25
     1.3     1.3
    1.54   25.15
Pier Skew, UpSta & Num, DnSta & Num=  ,5020.9, 2 ,5020.9, 2 , 0 , 0 , 0 ,,
     1.3     1.3
    4.95   25.25
     1.3     1.3
    4.85   25.15
Pier Skew, UpSta & Num, DnSta & Num=  ,5034.8, 2 ,5034.8, 2 , 0 , 0 , 0 ,,
     1.3     1.3
   12.42   25.25
     1.3     1.3
   12.32   25.15
Abutment Skew #Up #Dn= , 2 , 2
  4934.7  4959.7
   24.24    8.78
  4934.7  4959.7
   24.14    8.68
Abutment Skew #Up #Dn= , 2 , 2
  5044.9 5046.99
   23.12   24.25
  5044.9 5046.99
   23.02   24.15
BR Coef= 1 , 1 , 0 ,1.25, 0 ,,,0.8,0,2,0,
WSPro=,,,, 1 ,,,, 0 ,,,, 0 ,,,,-1 ,-1 ,-1 , 0 , 0 , 0 , 0 , 0
BR U #Sta/Elev= 52
 4280.69    27.5  4280.8   27.51 4280.91   27.52  4289.1    28.1  4419.1    26.7
  4451.1   27.08  4452.9    27.1  4726.3   23.49  4730.5   23.29  4731.1   23.26
  4795.3   20.14    4797   20.06  4864.3   13.98  4866.6   13.98  4934.7   14.08
 4934.81   14.08  4934.9   14.08  4946.4    14.1  4957.3    9.57  4959.7    8.78
  4969.4    5.58  4982.1    5.05  4983.4    4.97  4989.1    3.18  4995.6    1.56
  5002.1    -.11    5008    2.98  5010.8    3.47  5013.9    5.55  5020.9    5.99
  5034.9   13.84  5044.8   23.03  5044.9   23.12  5046.7   23.36 5046.79   23.37
  5046.9   23.38    5047    23.4  5053.7   24.28    5114   24.15  5143.2      24
  5208.2   23.66  5283.9   23.21  5353.4   25.46  5356.3   25.53  5356.4   25.54
 5400.69   26.67  5400.8   26.68 5400.91   26.68  5413.4      27  5478.6   26.81
    5481    26.8  5566.2    26.1
BR U #Mann= 5
 4280.69      .2  4451.1      .1  4946.4    .045  5034.9      .1  5478.6      .2
BR U Banks=4946.4,5034.9
BR D #Sta/Elev= 52
 4280.69    27.4  4280.8   27.41 4280.91   27.42  4289.1      28  4419.1    26.6
  4451.1   26.98  4452.9      27  4726.3   23.39  4730.5   23.19  4731.1   23.16
  4795.3   20.04    4797   19.96  4864.3   13.88  4866.6   13.88  4934.7   13.98
 4934.81   13.98  4934.9   13.98  4946.4      14  4957.3    9.47  4959.7    8.68
  4969.4    5.48  4982.1    4.95  4983.4    4.87  4989.1    3.08  4995.6    1.46
  5002.1    -.21    5008    2.88  5010.8    3.37  5013.9    5.45  5020.9    5.89
  5034.9   13.74  5044.8   22.93  5044.9   23.02  5046.7   23.26 5046.79   23.27
  5046.9   23.28    5047    23.3  5053.7   24.18    5114   24.05  5143.2    23.9
  5208.2   23.56  5283.9   23.11  5353.4   25.36  5356.3   25.43  5356.4   25.44
 5400.69   26.57  5400.8   26.58 5400.91   26.58  5413.4    26.9  5478.6   26.71
    5481    26.7  5566.2      26
BR D #Mann= 5
 4280.69      .2  4451.1      .1  4946.4    .045  5034.9      .1  5478.6      .2
BR D Banks=4946.4,5034.9
BC Design=,, 0 ,, 0 ,,,,,,
BC HTab HWMax=28.1
BC Use User HTab Curves=0
BC User HTab FreeFlow(D)= 0

Type RM Length L Ch R = 1 ,1487.7  ,29.9,29.9,29.9
BEGIN DESCRIPTION:
Downstream Section of Bridge/Culvert/Weir
END DESCRIPTION:
XS GIS Cut Line= 5
      3153420.17     13820044.04       3153679.7     13819724.61
      3153822.42     13819551.47      3154065.75     13819291.77
      3154252.44     13819065.08
#Sta/Elev= 26
 4280.69   27.44  4289.1   28.04  4419.1   26.64  4451.1   27.02  4726.3   23.43
    4797      20  4864.3   13.92  4946.4   14.04  4957.3    9.51  4969.4    5.52
  4983.4    4.91  4989.1    3.12  5002.1    -.17    5008    2.92  5010.8    3.41
  5013.9    5.49  5020.9    5.93  5034.9   13.78  5044.9   23.06  5053.7   24.22
    5114   24.09  5283.9   23.15  5353.4    25.4  5413.4   26.94  5478.6   26.75
  5566.2   26.04
#Mann= 5 , 1 , 0
 4280.69      .2       0  4451.1      .1       0  4946.4    .045       0
  5034.9      .1       0  5478.6      .2       0
#XS Ineff= 2 , 0
       0  4924.5    27.2    5057       0    27.4
Permanent Ineff=
       F       F
Bank Sta=4946.4,5034.9
XS Rating Curve= 0 ,0
Exp/Cntr=0.5,0.3

Type RM Length L Ch R = 1 ,1457.8  ,75.2,75.2,75.2
BEGIN DESCRIPTION:
Upstream Section of Bridge/Culvert/Weir
END DESCRIPTION:
XS GIS Cut Line= 4
      3153500.42     13819957.75      3153833.03     13819582.08
      3154137.19     13819238.15      3154210.31     13819165.01
#Sta/Elev= 30
    4397   28.16    4497   26.66    4557   24.56  4598.7   23.95  4614.5   24.26
  4624.5   23.56  4767.6   21.94  4871.2   21.74  4925.4   20.74  4942.2   21.06
  4960.8   12.73  4971.7    8.49  4990.1       3  4991.5    1.19  4994.9     .06
  5000.2    -.07  5006.9     .78  5009.8    3.01    5017    5.26  5026.7     9.9
  5029.1   10.67  5039.4   12.18  5066.4   21.62  5092.7   20.34 5151.71   22.38
  5368.6   25.86  5404.2   26.99  5418.6   27.06  5448.6   25.86  5461.3   26.06
#Mann= 5 , 1 , 0
    4397      .2       0  4598.7      .1       0  4971.7    .045       0
  5026.7      .1       0  5404.2      .2       0
#XS Ineff= 2 , 0
       0  4958.7      23  5049.3       0    23.6
Permanent Ineff=
       F       F
Bank Sta=4971.7,5026.7
XS Rating Curve= 0 ,0
Exp/Cntr=0.5,0.3

Type RM Length L Ch R = 3 ,1420.2  ,,,
BEGIN DESCRIPTION:
GALVESTON ROAD
Structure ID: C03-1
END DESCRIPTION:
Bridge Culvert--1,0,-1,-1, 0
Deck Dist Width WeirC Skew NumUp NumDn MinLoCord MaxHiCord MaxSubmerge Is_Ogee
10,55.2,2.6,0, 36, 36, , , 0.95, 0, 1,1,,
    4397    4497    4557  4564.5  4604.5  4614.5  4624.5  4720.4  4767.6  4818.8
 4852.89    4853  4871.2  4925.4  4942.2  4950.5  4960.8  4968.7  4968.8  5008.1
 5039.09  5039.2  5053.5  5066.4  5092.7  5148.1  5151.6 5151.71  5167.7  5205.4
  5274.3  5368.6  5398.6  5418.6  5448.6  5461.3
    28.2    26.7    24.6    24.5   24.15   24.31      24   23.24   23.03   22.95
   22.97   25.47   25.49   25.08   24.95   24.89   24.81   24.75   24.75   25.37
   24.76   24.76   24.99    25.2    25.6   26.03   26.06   23.56   23.68   24.14
   25.05   26.42   27.01    27.1    25.9    26.1
    28.2    26.7    24.6    24.5    23.9    24.3    23.6   22.61   21.98   21.73
   21.76   21.76   21.78   20.78    21.1   17.16   12.77    9.58   18.05   18.67
   18.06   12.19   16.97   21.66   20.38   22.34   22.41   22.42   22.75   23.54
   24.26    25.9      27    27.1    25.9    26.1
    4397    4497    4557  4564.5  4604.5  4614.5  4624.5  4720.4  4767.6  4818.8
 4852.89    4853  4871.2  4925.4  4942.2  4950.5  4960.8  4968.7  4968.8  5008.1
 5039.09  5039.2  5053.5  5066.4  5092.7  5148.1  5151.6 5151.71  5167.7  5205.4
  5274.3  5368.6  5398.6  5418.6  5448.6  5461.3
    28.2    26.7    24.6    24.5   24.15   24.31      24   23.24   23.03   22.95
   22.97   25.47   25.49   25.08   24.95   24.89   24.81   24.75   24.75   25.37
   24.76   24.76   24.99    25.2    25.6   26.03   26.06   23.56   23.68   24.14
   25.05   26.42   27.01    27.1    25.9    26.1
   27.93   26.43   24.33   24.23   23.63   24.03   23.33   22.34   21.71   21.46
   21.49   21.49   21.51   20.51   20.83   16.89    12.5    9.31   17.78    18.4
   17.79   11.92    16.7   21.39   20.11   22.07   22.14   22.15   22.48   23.27
   23.99   25.63   26.73   26.83   25.63   25.83
Pier Skew, UpSta & Num, DnSta & Num=  ,4991.5, 2 ,4991.5, 2 , 0 , 0 , 0 ,,
     1.2     1.2
     .03   19.42
     1.2     1.2
    -.24   19.15
Pier Skew, UpSta & Num, DnSta & Num=  ,5017, 2 ,5017, 2 , 0 , 0 , 0 ,,
     1.2     1.2
    4.11   19.51
     1.2     1.2
    3.84   19.24
BR Coef= 1 , 1 , 0 ,1.25, 0 ,,,0.8,0,2,0,
WSPro=,,,, 1 ,,,, 0 ,,,, 0 ,,,,-1 ,-1 ,-1 , 0 , 0 , 0 , 0 , 0
BR U #Sta/Elev= 64
    4397    28.2    4497    26.7    4557    24.6  4564.5    24.5  4598.7   23.99
  4604.5    23.9  4614.5    24.3  4624.5    23.6  4719.6   22.62  4720.4   22.61
  4765.5   22.01  4767.6   21.98  4818.8   21.73  4819.5   21.73 4852.89   21.76
    4853   21.76 4853.11   21.76  4871.2   21.78  4872.4   21.76  4925.4   20.78
  4942.2    21.1  4950.5   17.16  4960.8   12.77  4968.5    9.66 4968.61    9.62
  4968.7    9.58  4968.8    9.54  4968.9    9.51  4971.7    8.53  4990.1    3.04
  4991.5    1.23  4994.9      .1  5000.2    -.03  5006.9     .82  5008.1    1.74
  5009.8    3.05    5017     5.3  5026.7    9.94  5029.1   10.71  5038.4   12.07
 5039.09   12.17  5039.2   12.19  5039.3   12.21  5039.4   12.22  5053.5   16.97
  5066.4   21.66  5089.1   20.56  5092.7   20.38  5148.1   22.34 5151.49   22.41
  5151.6   22.41 5151.71   22.42  5167.7   22.75  5205.4   23.54  5224.6   23.74
  5274.3   24.26  5279.7   24.35  5357.8   25.71  5368.6    25.9  5398.6      27
  5404.2   27.03  5418.6    27.1  5448.6    25.9  5461.3    26.1
BR U #Mann= 5
    4397      .2  4598.7      .1  4971.7    .045  5026.7      .1  5404.2      .2
BR U Banks=4971.7,5026.7
BR D #Sta/Elev= 64
    4397   27.93    4497   26.43    4557   24.33  4564.5   24.23  4598.7   23.72
  4604.5   23.63  4614.5   24.03  4624.5   23.33  4719.6   22.35  4720.4   22.34
  4765.5   21.74  4767.6   21.71  4818.8   21.46  4819.5   21.46 4852.89   21.49
    4853   21.49 4853.11   21.49  4871.2   21.51  4872.4   21.49  4925.4   20.51
  4942.2   20.83  4950.5   16.89  4960.8    12.5  4968.5    9.39 4968.61    9.35
  4968.7    9.31  4968.8    9.27  4968.9    9.24  4971.7    8.26  4990.1    2.77
  4991.5     .96  4994.9    -.17  5000.2     -.3  5006.9     .55  5008.1    1.47
  5009.8    2.78    5017    5.03  5026.7    9.67  5029.1   10.44  5038.4    11.8
 5039.09    11.9  5039.2   11.92  5039.3   11.94  5039.4   11.95  5053.5    16.7
  5066.4   21.39  5089.1   20.29  5092.7   20.11  5148.1   22.07 5151.49   22.14
  5151.6   22.14 5151.71   22.15  5167.7   22.48  5205.4   23.27  5224.6   23.47
  5274.3   23.99  5279.7   24.08  5357.8   25.44  5368.6   25.63  5398.6   26.73
  5404.2   26.76  5418.6   26.83  5448.6   25.63  5461.3   25.83
BR D #Mann= 5
    4397      .2  4598.7      .1  4971.7    .045  5026.7      .1  5404.2      .2
BR D Banks=4971.7,5026.7
BC Design=,, 0 ,, 0 ,,,,,,
BC HTab HWMax=28.16
BC Use User HTab Curves=0
BC User HTab FreeFlow(D)= 0

Type RM Length L Ch R = 1 ,1382.6  ,15.5,15.5,15.5
BEGIN DESCRIPTION:
Downstream Section of Bridge/Culvert/Weir
END DESCRIPTION:
XS GIS Cut Line= 4
      3153560.47       13820003.      3153893.09     13819627.34
      3154197.25     13819283.41      3154270.36     13819210.27
#Sta/Elev= 30
    4397   28.24    4497   26.74    4557   24.64  4598.7   24.03  4614.5   24.34
  4624.5   23.64  4767.6   22.02  4871.2   21.82  4925.4   20.82  4942.2   21.14
  4960.8   12.81  4971.7    8.57  4990.1    3.08  4991.5    1.27  4994.9     .14
  5000.2     .01  5006.9     .86  5009.8    3.09    5017    5.34  5026.7    9.98
  5029.1   10.75  5039.4   12.26  5066.4    21.7  5092.7   20.42 5151.71   22.46
  5368.6   25.94  5404.2   27.07  5418.6   27.14  5448.6   25.94  5461.3   26.14
#Mann= 5 , 1 , 0
    4397      .2       0  4598.7      .1       0  4971.7    .045       0
  5026.7      .1       0  5404.2      .2       0
#XS Ineff= 2 , 0
       0  4958.7    22.8  5049.3       0    23.4
Permanent Ineff=
       F       F
Bank Sta=4971.7,5026.7
XS Rating Curve= 0 ,0
Exp/Cntr=0.5,0.3

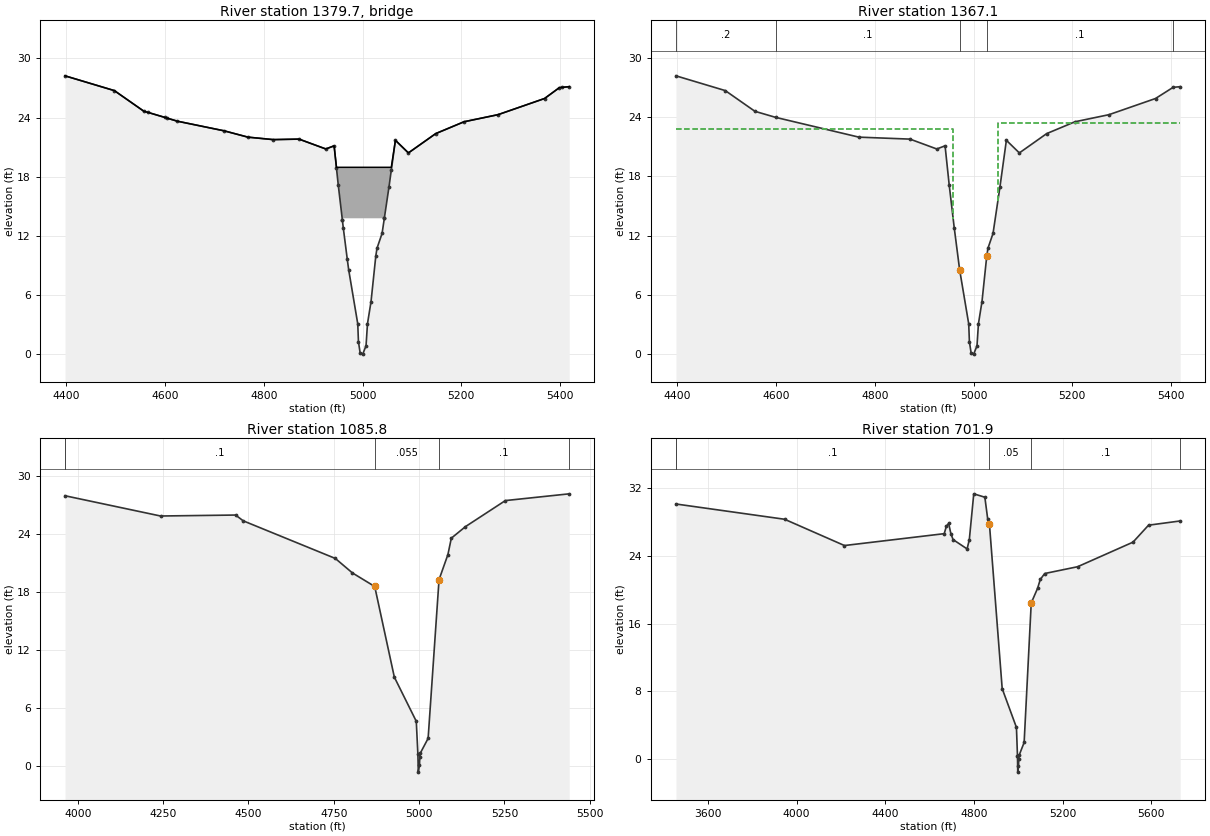
Type RM Length L Ch R = 3 ,1379.7  ,,,
BEGIN DESCRIPTION:
GALVESTON ROAD CROSS MEMBER
END DESCRIPTION:
Bridge Culvert--1,0,-1,-1, 0
Deck Dist Width WeirC Skew NumUp NumDn MinLoCord MaxHiCord MaxSubmerge Is_Ogee
10,5.2,2.6,0, 43, 43, , , 0.95, 0, 1,1,,
    4397    4497    4557  4564.5  4598.7  4604.5  4624.5 4719.52 4767.62 4818.82
 4871.22 4925.42 4942.22 4947.02 4950.52 4958.93 4959.02 4960.82 4968.92 4971.72
 4990.12 4991.52 4994.92 5000.22 5006.92 5009.82 5017.02 5026.72 5029.12 5039.42
 5043.91 5044.02 5053.52 5058.02 5066.42 5092.72 5148.12 5205.42 5274.32  5368.6
  5398.6  5404.2  5418.6
   28.23   26.73   24.63   24.53   24.02   23.93   23.63   22.65   22.01   21.76
   21.81   20.81   21.13   18.95   18.95   18.95   18.95   18.95   18.95   18.95
   18.95   18.95   18.95   18.95   18.95   18.95   18.95   18.95   18.95   18.95
   18.95   18.95   18.95   18.95   21.69   20.41   22.37   23.57   24.29   25.93
   27.03   27.06   27.13
   28.23   26.73   24.63   24.53   24.02   23.93   23.63   22.65   22.01   21.76
   21.81   20.81   21.13   18.85   17.19   13.61   13.78   13.78   13.78   13.78
   13.78   13.78   13.78   13.78   13.78   13.78   13.78   13.78   13.78   13.78
   13.78    13.8      17   18.64   21.69   20.41   22.37   23.57   24.29   25.93
   27.03   27.06   27.13
    4397    4497    4557  4564.5  4598.7  4604.5  4624.5 4719.52 4767.62 4818.82
 4871.22 4925.42 4942.22 4947.02 4950.52 4958.93 4959.02 4960.82 4968.92 4971.72
 4990.12 4991.52 4994.92 5000.22 5006.92 5009.82 5017.02 5026.72 5029.12 5039.42
 5043.91 5044.02 5053.52 5058.02 5066.42 5092.72 5148.12 5205.42 5274.32  5368.6
  5398.6  5404.2  5418.6
   28.23   26.73   24.63   24.53   24.02   23.93   23.63   22.65   22.01   21.76
   21.81   20.81   21.13   18.95   18.95   18.95   18.95   18.95   18.95   18.95
   18.95   18.95   18.95   18.95   18.95   18.95   18.95   18.95   18.95   18.95
   18.95   18.95   18.95   18.95   21.69   20.41   22.37   23.57   24.29   25.93
   27.03   27.06   27.13
   28.23   26.73   24.63   24.53   24.02   23.93   23.63   22.65   22.01   21.76
   21.81   20.81   21.13   18.85   17.19   13.61   13.78   13.78   13.78   13.78
   13.78   13.78   13.78   13.78   13.78   13.78   13.78   13.78   13.78   13.78
   13.78    13.8      17   18.64   21.69   20.41   22.37   23.57   24.29   25.93
   27.03   27.06   27.13
BR Coef= 1 , 1 , 0 ,1.25, 0 ,,,0.8,0,2,0,
WSPro=,,,, 1 ,,,, 0 ,,,, 0 ,,,,-1 ,-1 ,-1 , 0 , 0 , 0 , 0 , 0
BR U #Sta/Elev= 43
    4397   28.23    4497   26.73    4557   24.63  4564.5   24.53  4598.7   24.02
  4604.5   23.93  4624.5   23.63 4719.52   22.65 4767.62   22.01 4818.82   21.76
 4871.22   21.81 4925.42   20.81 4942.22   21.13 4947.02   18.85 4950.52   17.19
 4958.93   13.61 4959.02   13.57 4960.82    12.8 4968.92    9.61 4971.72    8.56
 4990.12    3.07 4991.52    1.26 4994.92     .13 5000.22       0 5006.92     .85
 5009.82    3.08 5017.02    5.33 5026.72    9.97 5029.12   10.74 5039.42   12.25
 5043.91   13.76 5044.02    13.8 5053.52      17 5058.02   18.64 5066.42   21.69
 5092.72   20.41 5148.12   22.37 5205.42   23.57 5274.32   24.29  5368.6   25.93
  5398.6   27.03  5404.2   27.06  5418.6   27.13
BR U #Mann= 5
    4397      .2  4598.7      .1 4971.72    .045 5026.72      .1  5404.2      .2
BR U Banks=4971.72,5026.72
BR D #Sta/Elev= 43
    4397   28.23    4497   26.73    4557   24.63  4564.5   24.53  4598.7   24.02
  4604.5   23.93  4624.5   23.63 4719.52   22.65 4767.62   22.01 4818.82   21.76
 4871.22   21.81 4925.42   20.81 4942.22   21.13 4947.02   18.85 4950.52   17.19
 4958.93   13.61 4959.02   13.57 4960.82    12.8 4968.92    9.61 4971.72    8.56
 4990.12    3.07 4991.52    1.26 4994.92     .13 5000.22       0 5006.92     .85
 5009.82    3.08 5017.02    5.33 5026.72    9.97 5029.12   10.74 5039.42   12.25
 5043.91   13.76 5044.02    13.8 5053.52      17 5058.02   18.64 5066.42   21.69
 5092.72   20.41 5148.12   22.37 5205.42   23.57 5274.32   24.29  5368.6   25.93
  5398.6   27.03  5404.2   27.06  5418.6   27.13
BR D #Mann= 5
    4397      .2  4598.7      .1 4971.72    .045 5026.72      .1  5404.2      .2
BR D Banks=4971.72,5026.72
BC Design=,, 0 ,, 0 ,,,,,,
BC HTab HWMax=28.24
BC Use User HTab Curves=0
BC User HTab FreeFlow(D)= 0

Type RM Length L Ch R = 1 ,1367.1  ,281.3,281.3,281.3
BEGIN DESCRIPTION:
Downstream Section of Bridge/Culvert/Weir
END DESCRIPTION:
XS GIS Cut Line= 4
      3153568.34      13820012.9      3153926.34     13819662.42
      3154105.23     13819468.63      3154292.45     13819292.77
#Sta/Elev= 30
    4397   28.21    4497   26.71    4557   24.61  4598.7      24 4767.62   21.99
 4871.22   21.79 4925.42   20.79 4942.22   21.11 4950.52   17.17 4960.82   12.78
 4971.72    8.54 4990.12    3.05 4991.52    1.24 4994.92     .11 5000.22    -.02
 5006.92     .83 5009.82    3.06 5017.02    5.31 5026.72    9.95 5029.12   10.72
 5039.42   12.23 5053.52   16.98 5066.42   21.67 5092.72   20.39 5148.12   22.35
 5205.42   23.55 5274.32   24.27  5368.6   25.91  5404.2   27.04  5418.6   27.11
#Mann= 5 , 1 , 0
    4397      .2       0  4598.7      .1       0 4971.72    .045       0
 5026.72      .1       0  5404.2      .2       0
#XS Ineff= 2 , 0
       0  4958.7    22.8  5049.3       0    23.4
Permanent Ineff=
       F       F
Bank Sta=4971.72,5026.72
XS Rating Curve= 0 ,0
Exp/Cntr=0.5,0.3

Type RM Length L Ch R = 1 ,1085.8  ,394.9,383.9,378.7
BEGIN DESCRIPTION:
Cross Section 1085.8-Interpolated
END DESCRIPTION:
XS GIS Cut Line= 6
      3153479.68     13820445.53       3153865.4     13820093.35
      3154060.35     13819906.78      3154290.95     13819602.82
      3154320.29     13819489.62      3154278.37     13819307.24
#Sta/Elev= 21
  3962.3      28  4242.3    25.9  4462.3      26  4484.6    25.4  4754.5    21.5
  4804.5      20    4870   18.59  4927.5    9.19  4991.8    4.61  4996.5    1.19
  4997.7    -.66    5001     .05  5002.4     .94  5003.6    1.31  5026.5    2.84
  5058.5    19.3  5084.5    21.9  5094.5    23.6    5136    24.8  5252.9    27.5
  5440.1    28.2
#Mann= 5 , 1 , 0
  3962.3      .2       0  3962.3      .1       0    4870    .055       0
  5058.5      .1       0  5440.1      .2       0
Bank Sta=4870,5058.5
XS Rating Curve= 0 ,0
Exp/Cntr=0.3,0.1

Type RM Length L Ch R = 1 ,701.9   ,0,0,0
BEGIN DESCRIPTION:
Cross Section 701.9
END DESCRIPTION:
XS GIS Cut Line= 6
      3153185.74     13820811.42        3154327.     13820183.03
      3154525.68      13819882.7      3154534.93     13819734.85
      3154396.31     13819526.92      3154299.28     13819337.48
#Sta/Elev= 30
  3456.3    30.1  3946.1    28.3  4216.1    25.2  4666.1    26.6  4676.1    27.5
  4686.1    27.8  4696.1    26.6  4706.1    25.9  4769.3    24.8  4779.3    25.9
  4799.3    31.3  4849.3    30.9  4862.2   28.33    4870   27.72  4927.5    8.32
  4991.8    3.74  4996.5     .32  4997.7   -1.53    5001    -.82  5002.4     .07
  5003.6     .44  5026.5    1.97  5058.5   18.43  5087.1   20.15  5099.3    21.2
  5119.4    21.9  5267.6    22.7  5517.5    25.6  5587.5    27.6  5730.3    28.1
#Mann= 5 , 1 , 0
  3456.3      .2       0  3456.3      .1       0    4870     .05       0
  5058.5      .1       0  5730.3      .2       0
Bank Sta=4870,5058.5
XS Rating Curve= 0 ,0
Exp/Cntr=0.3,0.1

Chan Stop Cuts=-1
Use User Specified Reach Order=0
Composite Channel Slope=5